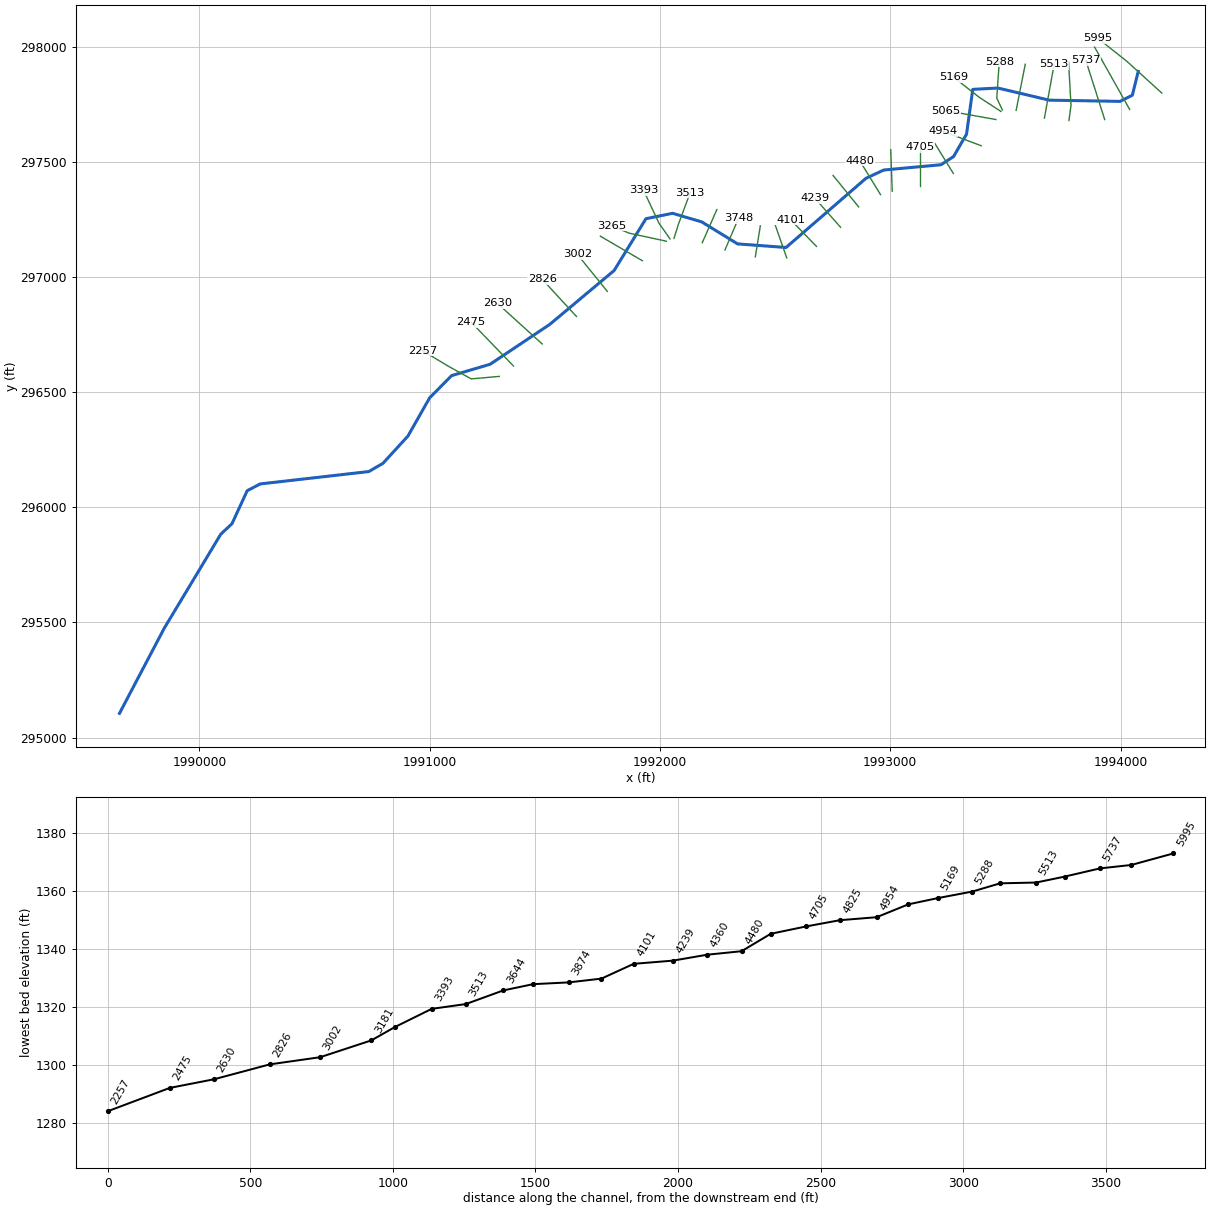
--- MEADOWCK_AE.prj (project) ---

Proj Title=MEADOWCK_AE
Current Plan=p01
Default Exp/Contr=0,0
English Units
Geom File=g01
Flow File=f01
Plan File=p01
BEGIN DESCRIPTION:
Stream Name: Meadow Creek
Flood Zone:  Detailed
Summers County, West Virginia
HEC-RAS Version: 5.0.7
Hydrology Method: Regression
Model Notes:
END DESCRIPTION:
DSS Export Rating Curves= 0
DSS Export Rating Curve Sorted= 0
DSS Export Volume Flow Curves= 0
DXF OffsetX= 0
DXF OffsetY= 0
DXF ScaleX= 0
DXF ScaleY= 0

--- MEADOWCK_AE.p01 (plan) ---

Plan Title=Floodplain
Program Version=5.07
Short Identifier=Floodplain
Geom File=g01
Flow File=f01
Subcritical Flow
K Sum by GR= 0
Std Step Tol= 0.01
Critical Tol= 0.01
Num of Std Step Trials= 20
Max Error Tol= 0.3
Flow Tol Ratio= 0.001
Split Flow NTrial= 30
Split Flow Tol= 0.02
Split Flow Ratio= 0.02
Log Output Level= 0
Friction Slope Method= 1
Unsteady Friction Slope Method= 2
Unsteady Bridges Friction Slope Method= 1
Parabolic Critical Depth
Global Vel Dist= 0 , 0 , 0
Global Log Level= 0
CheckData=True
Encroach Param=-1 ,10,10, 2
Encroach River=MEADOWCK_AE
Encroach Reach=Main
Encroach Node=5995
       1      82   159.3
Encroach Node=5847
       1      25      80
Encroach Node=5737
       1      45   101.5
Encroach Node=5613
       1      40     116
Encroach Node=5513
       1    56.5     118
Encroach Node=5387
       1    52.5     123
Encroach Node=5288
       1      50     150
Encroach Node=5169
       1   83.81     178
Encroach Node=5065
       1      60     152
Encroach Node=4954
       1      44     115
Encroach Node=4825
       1    35.5      92
Encroach Node=4705
       1    32.9    97.3
Encroach Node=4582
       1      54   130.4
Encroach Node=4480
       1      60     118
Encroach Node=4360
       1      53     112
Encroach Node=4239
       1    52.4     123
Encroach Node=4101
       1    36.1     114
Encroach Node=3988
       1    21.3      86
Encroach Node=3874
       1    18.3    58.1
Encroach Node=3748
       1    22.9    79.3
Encroach Node=3644
       1    50.4   103.6
Encroach Node=3513
       1    76.3   138.3
Encroach Node=3393
       1     105     183
Encroach Node=3265
       1     123     205
Encroach Node=3181
       1    40.6     133
Encroach Node=3002
       1    30.7    82.8
Encroach Node=2826
       1    27.9    82.4
Encroach Node=2630
       1    21.8      96
Encroach Node=2475
       1      22     108
Encroach Node=2257
       1  121.01     225
Encroach Node=2091
       1     220   353.9
Encroach Node=1985
       1   319.4   411.4
Encroach Node=1870
       1     210     280
Encroach Node=1690
       1   241.6   317.9
Encroach Node=1615
       1  238.65  318.83
Encroach Node=1505
       1   346.3  444.45
Encroach Node=1343
       1     393     507
Encroach Node=1130
       1     400   498.1
Encroach Node=858
       1   386.5     497
Encroach Node=681
       1   367.5     486
Encroach Node=582
       1   377.5  461.55
Encroach Node=427
       1   341.6     425
Encroach Node=241
       1     290     430
Encroach Node=100
       1   158.5   557.7
Mapping Interval=1HOUR
Computation Time Step Use Courant=        0
Computation Time Step Use Time Series=    0
Computation Time Step Count To Double=0
Computation Time Step Max Doubling=0
Computation Time Step Max Halving=0
Computation Time Step Residence Courant=0
Run HTab= 0
Run UNet= 0
Run Sediment= 0
Run PostProcess= 0
Run WQNet= 0
Run RASMapper= 0
UNET Theta= 0
UNET Theta Warmup= 0
UNET ZTol= 0
UNET ZSATol= 0
UNET MxIter= 0
UNET Max Iter WO Improvement= 0
UNET MaxInSteps= 0
UNET DtIC= 0
UNET DtMin= 0
UNET MaxCRTS= 0
UNET WFStab= 0
UNET SFStab= 0
UNET WFX= 1
UNET SFX= 1
UNET 1D Methodology=Finite Difference
UNET DSS MLevel= 1
UNET Pardiso=0
UNET DZMax Abort= 0
UNET Use Existing IB Tables= 0
UNET Froude Reduction=False
UNET Froude Limit= 0
UNET Froude Power= 0
UNET D1 Cores= 0
UNET D2 Coriolis=0
UNET D2 Cores= 0
UNET D2 Theta= 1
UNET D2 Theta Warmup= 1
UNET D2 Z Tol= 0.01
UNET D2 Volume Tol= 0.01
UNET D2 Max Iterations= 20
UNET D2 Equation= 0
UNET D2 RampUpFraction=0.1
UNET D2 TimeSlices= 1
UNET D2 BCVolumeCheck=0
UNET D1D2 MaxIter= 0
UNET D1D2 ZTol=0.01
UNET D1D2 QTol=0.1
UNET D1D2 MinQTol=1
Write IC File= 0
Write IC File at Fixed DateTime=0
Write IC File at Sim End=0
Echo Input=False
Echo Parameters=False
Echo Output=False
Write Detailed= 0
HDF Write Warmup=0
HDF Write Time Slices=0
HDF Flush=0
HDF Face Node Velocities=0
HDF Compression= 1
HDF Chunk Size= 1
HDF Spatial Parts= 1
HDF Use Max Rows=0
HDF Fixed Rows= 1
Calibration Method= 0
Calibration Iterations= 20
Calibration Max Change=0.05
Calibration Tolerance=0.2
Calibration Maximum=1.5
Calibration Minimum=0.5
Calibration Optimization Method= 1
WQ AD Non Conservative
WQ ULTIMATE=-1
WQ Max Comp Step=1HOUR
WQ Output Interval=15MIN
WQ Output Selected Increments= 0
WQ Output face flow=0
WQ Output face velocity=0
WQ Output face area=0
WQ Output face dispersion=0
WQ Output cell volume=0
WQ Output cell surface area=0
WQ Output cell continuity=0
WQ Output cumulative cell continuity=0
WQ Output face conc=0
WQ Output face dconc_dx=0
WQ Output face courant=0
WQ Output face peclet=0
WQ Output face adv mass=0
WQ Output face disp mass=0
WQ Output cell mass=0
WQ Output cell source sink temp=0
WQ Output nsm pathways=0
WQ Output nsm derived pathways=0
WQ Output MaxMinRange=-1
WQ Daily Max Min Mean=-1
WQ Daily Range=0
WQ Daily Time=0
WQ Create Restart=0
WQ Fixed Restart=0
WQ System Summary=0
WQ Write To DSS=0
WQ Use Fixed Temperature=0
Sorting and Armoring Iterations= 10
XS Update Threshold= 0.02
Bed Roughness Predictor= 0
Hydraulics Update Threshold= 0.02
Energy Slope Method= 1
Volume Change Method= 1
Sediment Retention Method= 0
XS Weighting Method= 0
Number of US Weighted Cross Sections= 1
Number of DS Weighted Cross Sections= 1
Upstream XS Weight=0
Main XS Weight=1
Downstream XS Weight=0
Number of DS XS's Weighted with US Boundary= 1
Upstream Boundary Weight= 1
Weight of XSs Associated with US Boundary= 0
Number of US XS's Weighted with DS Boundary= 1
Downstream Boundary Weight= 0.5
Weight of XSs Associated with DS Boundary= 0.5
Percentile Method= 0
Sediment Output Level= 3
Mass or Volume Output= 0
Output Increment Type= 1
Profile and TS Output Increment= 1
XS Output Flag= 0
XS Output Increment= 10
Write Gradation File= 0
Read Gradation Hotstart= 0
Write HDF5 File= 1
Write Binary Output= 1
Write DSS Sediment File= 0
SV Curve= 0
Specific Gage Flag= 0

--- MEADOWCK_AE.f01 (steady flow) ---

Flow Title=Flows
Program Version=5.07
Number of Profiles= 7
Profile Names=01pct,FW,10pct,04pct,02pct,0_2pct,01plus
River Rch & RM=MEADOWCK_AE,Main            ,5995
    4358    4358    2491    3190    3756    5860    6445
Boundary for River Rch & Prof#=MEADOWCK_AE,Main            , 1
Up Type= 0
Dn Type= 3
Dn Slope=0.01306
Boundary for River Rch & Prof#=MEADOWCK_AE,Main            , 2
Up Type= 0
Dn Type= 3
Dn Slope=0.01306
Boundary for River Rch & Prof#=MEADOWCK_AE,Main            , 3
Up Type= 0
Dn Type= 3
Dn Slope=0.01306
Boundary for River Rch & Prof#=MEADOWCK_AE,Main            , 4
Up Type= 0
Dn Type= 3
Dn Slope=0.01306
Boundary for River Rch & Prof#=MEADOWCK_AE,Main            , 5
Up Type= 0
Dn Type= 3
Dn Slope=0.01306
Boundary for River Rch & Prof#=MEADOWCK_AE,Main            , 6
Up Type= 0
Dn Type= 3
Dn Slope=0.01306
DSS Import GetInterval= 0
DSS Import GetPeak= 0
DSS Import FillOption= 0

--- MEADOWCK_AE.g01 (geometry) ---

Geom Title=Geometry
Program Version=5.07

River Reach=MEADOWCK_AE     ,Main
Reach XY= 30
     1994076.837      297893.032      1994051.38       297789.66
     1993997.908      297762.9241993690.50542265 297768.27488074
     1993467.473      297820.8161993358.31525748297815.192710584
     1993331.242      297620.563     1993274.818      297523.341
      1993220.13       297487.75     1992971.551      297464.788
     1992894.299      297428.642     1992547.387      297128.375
      1992337.04       297143.991992180.94587981297239.660396838
     1992054.556      297276.811     1991938.881      297253.375
     1991800.736       297028.27     1991520.313      296793.686
      1991262.06      296621.205      1991095.13      296571.952
     1990999.644      296475.598     1990905.276      296309.406
     1990797.045      296191.322     1990735.379      296155.256
     1990263.533      296101.466     1990207.109      296071.952
     1990141.137      295928.723      1990092.34      295883.144
     1989846.856      295474.713     1989652.483      295105.044

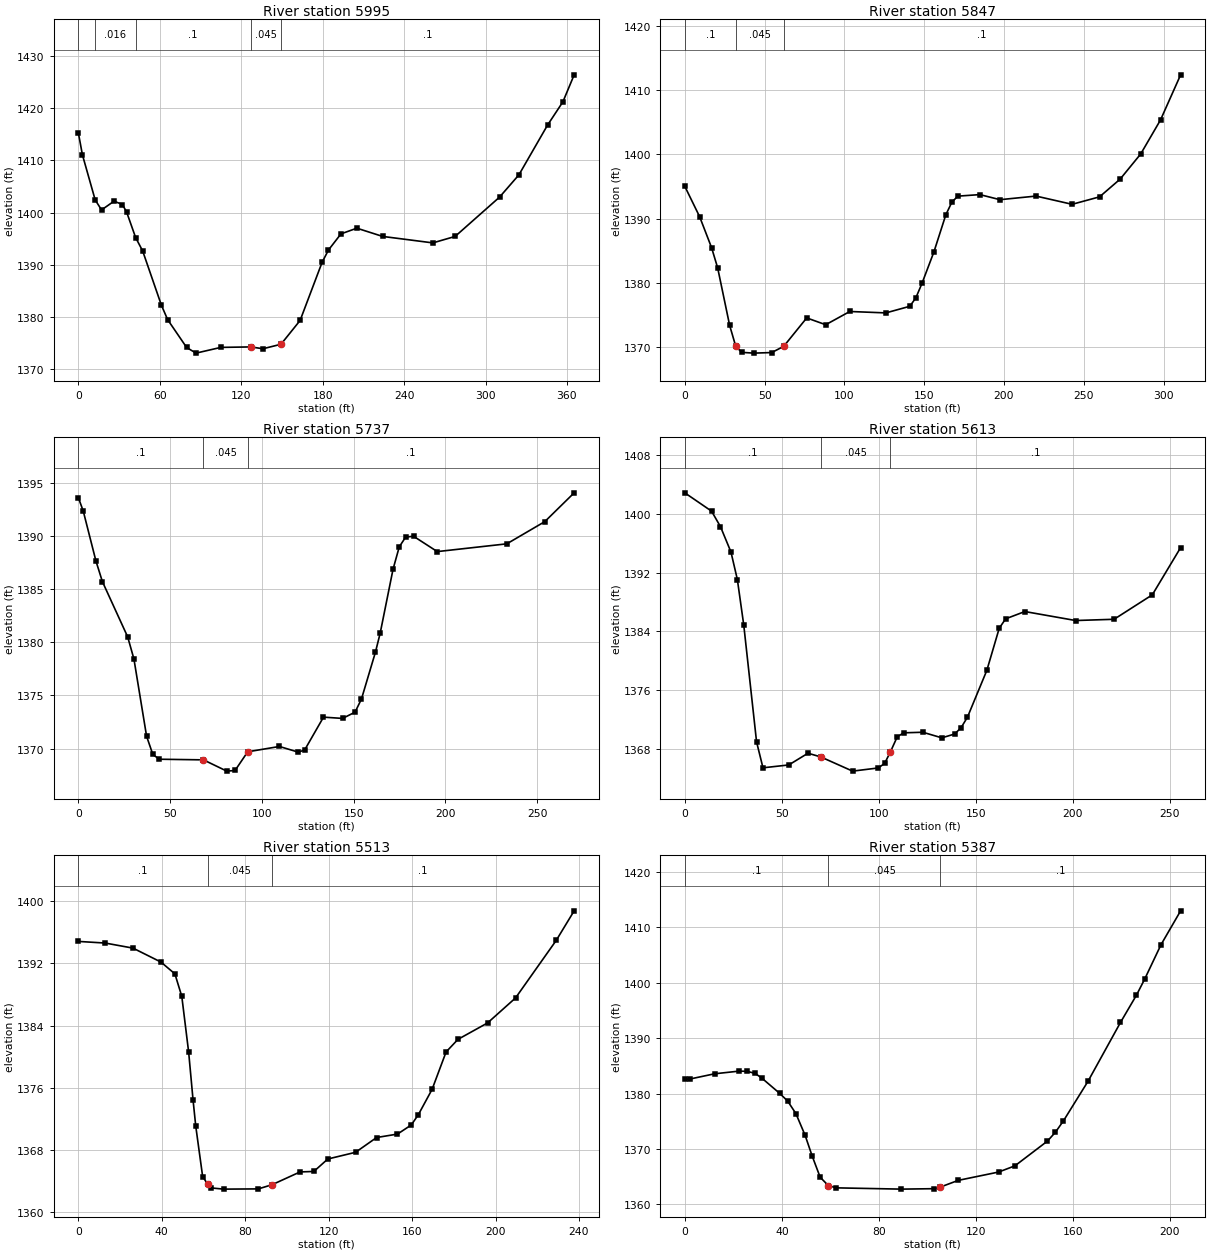
Type RM Length L Ch R = 1 ,5995    ,142.2,147.8,111.2
XS GIS Cut Line= 3
1994178.98589757297799.331470721 1994026.1354091297938.121066763
1993901.60060795298036.726212115
#Sta/Elev= 30
       0 1415.31       3 1411.09    12.4 1402.44    17.1 1400.51    26.3 1402.19
    32.5 1401.55    35.6 1400.09    42.2 1395.22    47.4 1392.64    61.2 1382.24
    65.8 1379.47    79.8 1374.13    86.7 1373.05     105 1374.15   127.1 1374.24
     136 1373.89   149.3 1374.75   163.4 1379.32   179.6 1390.47   184.3 1392.83
   193.5 1395.92   205.2 1397.01   224.2 1395.43   261.2 1394.19   277.6 1395.43
   310.3 1402.96   324.6 1407.24   345.7 1416.78     357 1421.24   365.3 1426.42
#Mann= 5 ,-1 , 0
       0      .1       0    12.4    .016       0    42.2      .1       0
   127.1    .045       0   149.3      .1       0
Bank Sta=127.1,149.3
XS Rating Curve= 0 ,0
Exp/Cntr(USF)=0,0
Exp/Cntr=0.3,0.1

Type RM Length L Ch R = 1 ,5847    ,113.8,110,92.4
XS GIS Cut Line= 3
1994039.76487168297727.7532747551994001.83941058297795.308002329
1993887.47044197297998.564770382
#Sta/Elev= 30
       0 1395.02     9.3 1390.29    16.8 1385.46    20.6 1382.32    28.1 1373.38
    31.9 1370.14    35.6 1369.18    43.2 1369.06    54.5 1369.15      62 1370.12
    76.4 1374.54    88.3 1373.48   103.4 1375.54     126 1375.32     141 1376.35
   144.8 1377.67   148.6  1379.9   156.1 1384.81   163.6 1390.61   167.4 1392.57
   171.1 1393.49   184.9 1393.73   197.5 1392.94   220.1  1393.5   242.7 1392.22
   259.9 1393.38   272.8 1396.14   285.7 1400.06   298.1 1405.35   310.7 1412.37
#Mann= 3 , 0 , 0
       0      .1       0    31.9    .045       0      62      .1       0
Bank Sta=31.9,62
XS Rating Curve= 0 ,0
Exp/Cntr(USF)=0,0
Exp/Cntr=0.3,0.1

Type RM Length L Ch R = 1 ,5737    ,137.8,124.1,109.7
XS GIS Cut Line= 2
1993931.33510213297684.0316545151993849.14448333297941.441834266
#Sta/Elev= 30
       0 1393.62     2.7 1392.34     9.6 1387.65    13.1 1385.72    26.9 1380.51
    30.3 1378.43    37.2 1371.16    40.6 1369.45    44.1    1369    68.2 1368.94
    80.9 1367.88    85.4 1367.94    92.3  1369.7   109.6  1370.2   119.8 1369.67
   123.3 1369.86   133.6 1372.96     144 1372.84   150.8 1373.43   154.3 1374.67
   161.9 1379.07   164.5 1380.87   171.5 1386.88   174.9 1388.99   178.4 1389.91
   182.7 1389.98   195.6 1388.54   233.5 1389.27   254.2 1391.36   270.2 1394.07
#Mann= 3 , 0 , 0
       0      .1       0    68.2    .045       0    92.3      .1       0
Bank Sta=68.2,92.3
XS Rating Curve= 0 ,0
Exp/Cntr(USF)=0,0
Exp/Cntr=0.3,0.1

Type RM Length L Ch R = 1 ,5613    ,106.6,100,90.3
XS GIS Cut Line= 3
1993775.98580066297679.5156864491993785.01773679 297745.44882021
1993774.17941344297934.216285361
#Sta/Elev= 30
       0 1402.83    13.8 1400.34    18.4 1398.23    23.8 1394.79    27.1 1391.05
    30.4 1384.86      37 1369.01    40.3 1365.49    53.6 1365.88    63.5 1367.47
    70.1 1366.97    86.5 1365.04    99.7 1365.47     103 1366.08     106 1367.66
   109.5 1369.69   112.8 1370.24   122.7 1370.32   132.5 1369.56   139.1 1370.08
   142.4 1370.93   145.7 1372.36   155.7 1378.72   162.1 1384.45   165.4 1385.72
   175.3 1386.71   201.5 1385.49   221.3 1385.66     241 1388.98   255.6 1395.39
#Mann= 3 , 0 , 0
       0      .1       0    70.1    .045       0     106      .1       0
Bank Sta=70.1,106
XS Rating Curve= 0 ,0
Exp/Cntr(USF)=0,0
Exp/Cntr=0.3,0.1

Type RM Length L Ch R = 1 ,5513    ,126.6,125.8,124.8
XS GIS Cut Line= 2
1993669.40895431297690.3540098071993711.85905413297924.281155616
#Sta/Elev= 30
       0 1394.82    12.9 1394.61    26.2 1393.96    39.6 1392.17    46.3 1390.65
    49.6 1387.76    52.9 1380.57      55 1374.44    56.3 1371.07    59.6 1364.61
    62.1  1363.6    63.5 1363.16    69.6    1363    86.3 1363.03    92.9 1363.57
   106.3 1365.21   112.9 1365.27   119.6 1366.87   132.9 1367.73     143 1369.63
     153 1370.07   159.6 1371.24     163 1372.56   169.6 1375.82   176.3 1380.62
     182 1382.24   196.2 1384.35   209.6 1387.56   229.1 1394.95   237.7 1398.75
#Mann= 3 , 0 , 0
       0      .1       0    62.1    .045       0    92.9      .1       0
Bank Sta=62.1,92.9
XS Rating Curve= 0 ,0
Exp/Cntr(USF)=0,0
Exp/Cntr=0.3,0.1

Type RM Length L Ch R = 1 ,5387    ,94.7,98.4,104.2
XS GIS Cut Line= 2
1993546.57462292297723.772173494 1993586.3151419297924.281155616
#Sta/Elev= 30
       0 1382.54     2.3 1382.64    12.3 1383.57    22.4 1384.05    25.7 1384.01
      29 1383.64    31.8 1382.77    39.1 1380.04    42.4 1378.64    45.8 1376.38
    49.6 1372.45    52.5 1368.72    55.8 1364.88    59.2 1363.36    62.5 1362.96
    89.3 1362.73   102.6 1362.81   105.4 1363.11   112.7 1364.31   129.4 1365.82
   136.1 1366.94   149.5 1371.41   152.8 1373.02   156.1 1375.07   166.2  1382.2
   179.6 1392.84   186.2 1397.78   189.6 1400.69   196.3 1406.88   204.4 1413.01
#Mann= 3 , 0 , 0
       0      .1       0    59.2    .045       0   105.4      .1       0
Bank Sta=59.2,105.4
XS Rating Curve= 0 ,0
Exp/Cntr(USF)=0,0
Exp/Cntr=0.3,0.1

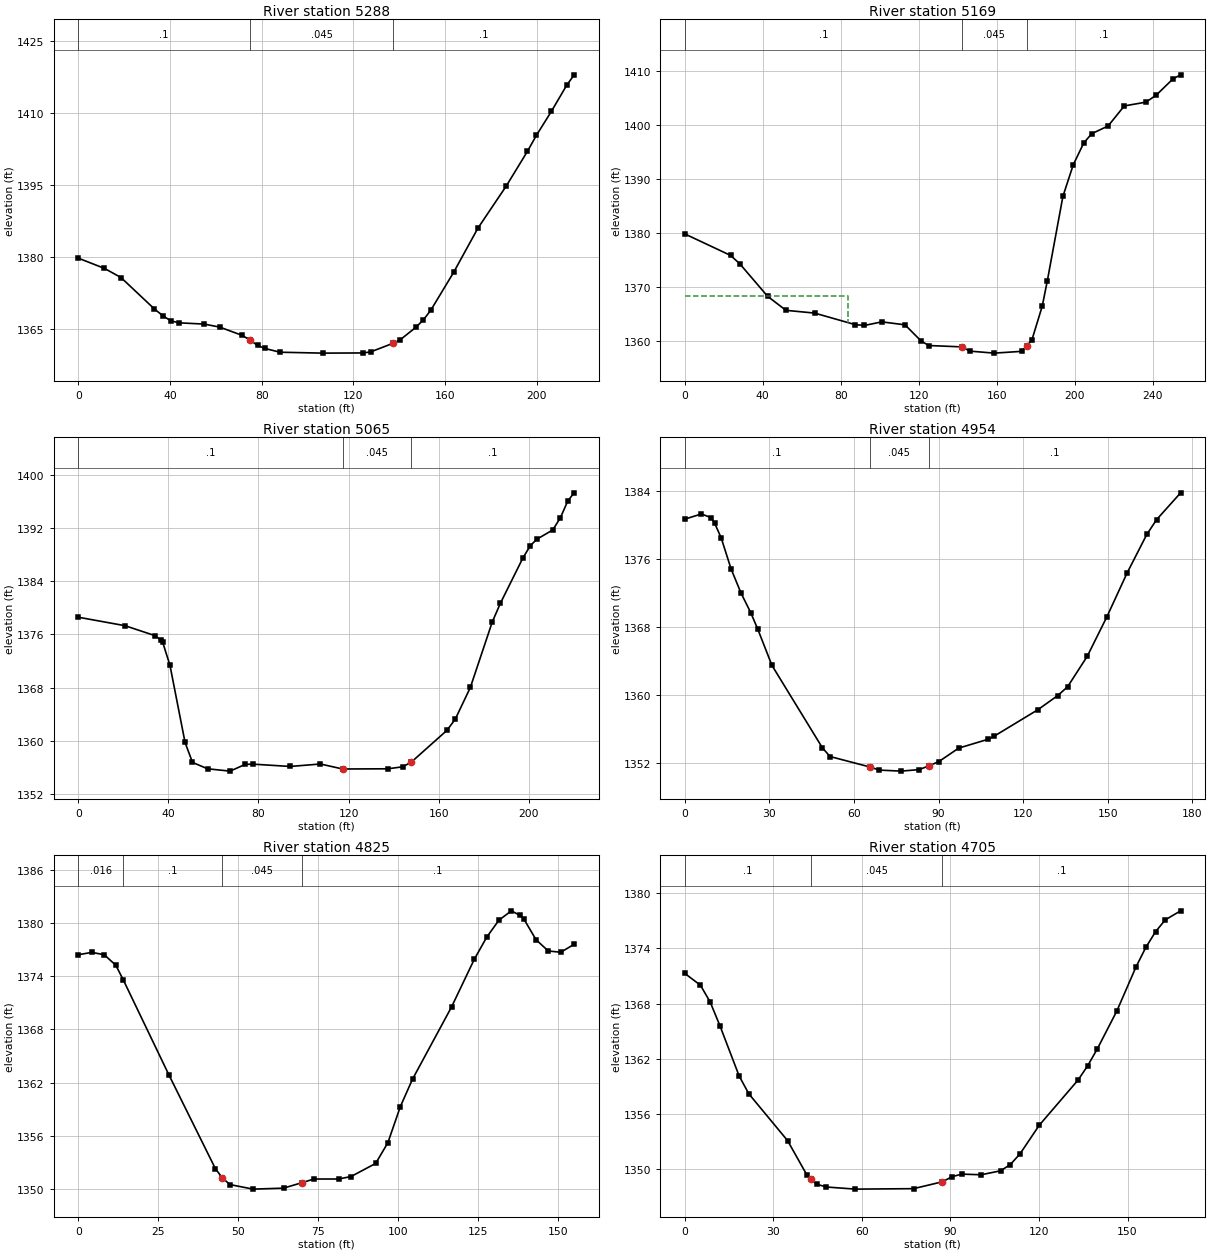
Type RM Length L Ch R = 1 ,5288    ,51.6,119,145.7
XS GIS Cut Line= 3
1993486.96384445 297725.578560721993462.57761689297777.060596671
1993473.41594025297936.022672587
#Sta/Elev= 30
       0 1379.69    11.4 1377.55    18.6 1375.65    33.2 1369.08    36.8  1367.7
    40.4 1366.59    44.1 1366.19    54.9 1365.93    61.7  1365.3    71.6 1363.55
    74.9 1362.58    78.2 1361.47    81.4 1360.84      88 1360.06   106.6 1359.87
   124.2 1359.91   127.5 1360.12   137.3 1361.93   140.4 1362.65   147.2 1365.24
   150.5 1366.79   153.8 1368.86   163.7 1376.71   174.3 1385.94   186.7 1394.76
   195.9 1401.97   199.8 1405.29   206.4 1410.35     213 1415.74   216.3 1417.95
#Mann= 3 , 0 , 0
       0      .1       0    74.9    .045       0   137.3      .1       0
Bank Sta=74.9,137.3
XS Rating Curve= 0 ,0
Exp/Cntr(USF)=0,0
Exp/Cntr=0.3,0.1

Type RM Length L Ch R = 1 ,5169    ,75.8,104.7,115.6
XS GIS Cut Line= 3
1993480.64148916297719.256205428  1993387.612547 297779.77017751
1993274.71334536  297868.2831516
#Sta/Elev= 30
       0 1379.78    23.5 1375.79    28.2 1374.24    42.5  1368.2    51.9  1365.6
    66.6 1365.09    87.5 1362.94    92.2  1362.8   101.1 1363.46     113 1362.91
   121.3 1359.89   125.2 1359.07   142.1 1358.82   146.3 1358.03   158.8 1357.66
   172.8 1357.99   175.5    1359   178.1 1360.12   183.4 1366.38     186 1371.07
     194 1386.74   199.3  1392.6   204.7 1396.66   208.8 1398.38   217.2 1399.81
   225.5 1403.53   236.6 1404.23   241.9 1405.54   250.5 1408.55   254.4  1409.3
#Mann= 3 , 0 , 0
       0      .1       0   142.1    .045       0   175.5      .1       0
#XS Ineff= 2 , 0
           83.81 1368.24
Permanent Ineff=
       F       F
Bank Sta=142.1,175.5
XS Rating Curve= 0 ,0
Exp/Cntr(USF)=0,0
Exp/Cntr=0.3,0.1

Type RM Length L Ch R = 1 ,5065    ,116,111,103.3
XS GIS Cut Line= 2
1993458.96484244297684.0316545151993242.19837528297722.868979881
#Sta/Elev= 30
       0 1378.58    20.7 1377.31    34.1 1375.81    36.8 1375.12    37.4 1374.89
    40.7 1371.35    47.4 1359.78    50.7 1356.79    57.4 1355.83    67.4 1355.48
    74.1 1356.49    77.4 1356.53    94.1 1356.18   107.5 1356.55   117.4  1355.8
   137.4 1355.83   144.1 1356.13   147.9 1356.84   163.7  1361.6   167.4 1363.28
   174.1 1368.04   183.8 1377.84   187.4 1380.65   197.4 1387.45   200.7 1389.31
   203.6 1390.28   210.7 1391.68   214.1 1393.52   217.4 1396.05   220.2 1397.25
#Mann= 3 , 0 , 0
       0      .1       0   117.4    .045       0   147.9      .1       0
Bank Sta=117.4,147.9
XS Rating Curve= 0 ,0
Exp/Cntr(USF)=0,0
Exp/Cntr=0.3,0.1

Type RM Length L Ch R = 1 ,4954    ,142.2,129.1,111.5
XS GIS Cut Line= 2
1993394.83809591297570.2292592561993230.45685831297632.549618564
#Sta/Elev= 30
       0 1380.74     5.9 1381.35     9.4  1380.9    10.6 1380.25    12.9 1378.53
    16.4 1374.88    19.9 1372.05    23.4  1369.7    25.9 1367.75    30.9  1363.5
    48.8 1353.78    51.5 1352.76    65.5 1351.54      69 1351.16    76.7 1351.04
    83.1 1351.22    86.6 1351.67    90.1 1352.17    97.1 1353.75   107.6  1354.8
   109.8 1355.18   125.2 1358.28   132.2 1359.94   135.7 1360.97   142.7 1364.58
   149.7 1369.26   156.8 1374.38   163.8 1378.93   167.3 1380.69   175.8 1383.84
#Mann= 3 , 0 , 0
       0      .1       0    65.5    .045       0    86.6      .1       0
Bank Sta=65.5,86.6
XS Rating Curve= 0 ,0
Exp/Cntr(USF)=0,0
Exp/Cntr=0.3,0.1

Type RM Length L Ch R = 1 ,4825    ,135.2,119.4,100.9
XS GIS Cut Line= 2
1993273.81015174297450.1045087051993192.52272656297581.970776227
#Sta/Elev= 30
       0 1376.42     4.2 1376.69     8.1 1376.42    11.7 1375.24      14 1373.62
    28.3 1362.88    42.8 1352.33      45 1351.26    47.4 1350.52    54.6 1350.01
    64.1 1350.12    69.8 1350.73    73.6 1351.15    81.3 1351.15    85.2 1351.43
    92.9 1352.91    96.7 1355.24   100.6 1359.31   104.4  1362.4   116.6 1370.54
   123.7 1375.91   127.6 1378.41   131.4 1380.32   135.3 1381.37     138 1380.85
   139.1  1380.5     143 1378.11   146.8 1376.85   150.7  1376.7   154.9  1377.6
#Mann= 4 ,-1 , 0
       0    .016       0      14      .1       0      45    .045       0
    69.8      .1       0
Bank Sta=45,69.8
XS Rating Curve= 0 ,0
Exp/Cntr(USF)=0,0
Exp/Cntr=0.3,0.1

Type RM Length L Ch R = 1 ,4705    ,122.6,123.2,124.6
XS GIS Cut Line= 2
1993128.39598002297395.9128919161993128.39598002297563.906903964
#Sta/Elev= 30
       0 1371.27     5.3 1369.99     8.6 1368.16    11.9 1365.59    18.4 1360.14
    21.7 1358.19    34.8 1353.12    41.4 1349.36    42.9 1348.89    44.7 1348.37
      48 1348.07    57.8 1347.84    77.5 1347.89    87.3 1348.64    90.6  1349.2
    93.9 1349.47   100.4  1349.4     107 1349.83   110.3 1350.51   113.6 1351.68
   120.1 1354.78   133.3 1359.71   136.5 1361.24   139.8 1363.09   146.4  1367.2
   152.9 1371.99   156.2 1374.09   159.5  1375.8   162.8 1377.09     168 1378.07
#Mann= 3 , 0 , 0
       0      .1       0    42.9    .045       0    87.3      .1       0
Bank Sta=42.9,87.3
XS Rating Curve= 0 ,0
Exp/Cntr(USF)=0,0
Exp/Cntr=0.3,0.1

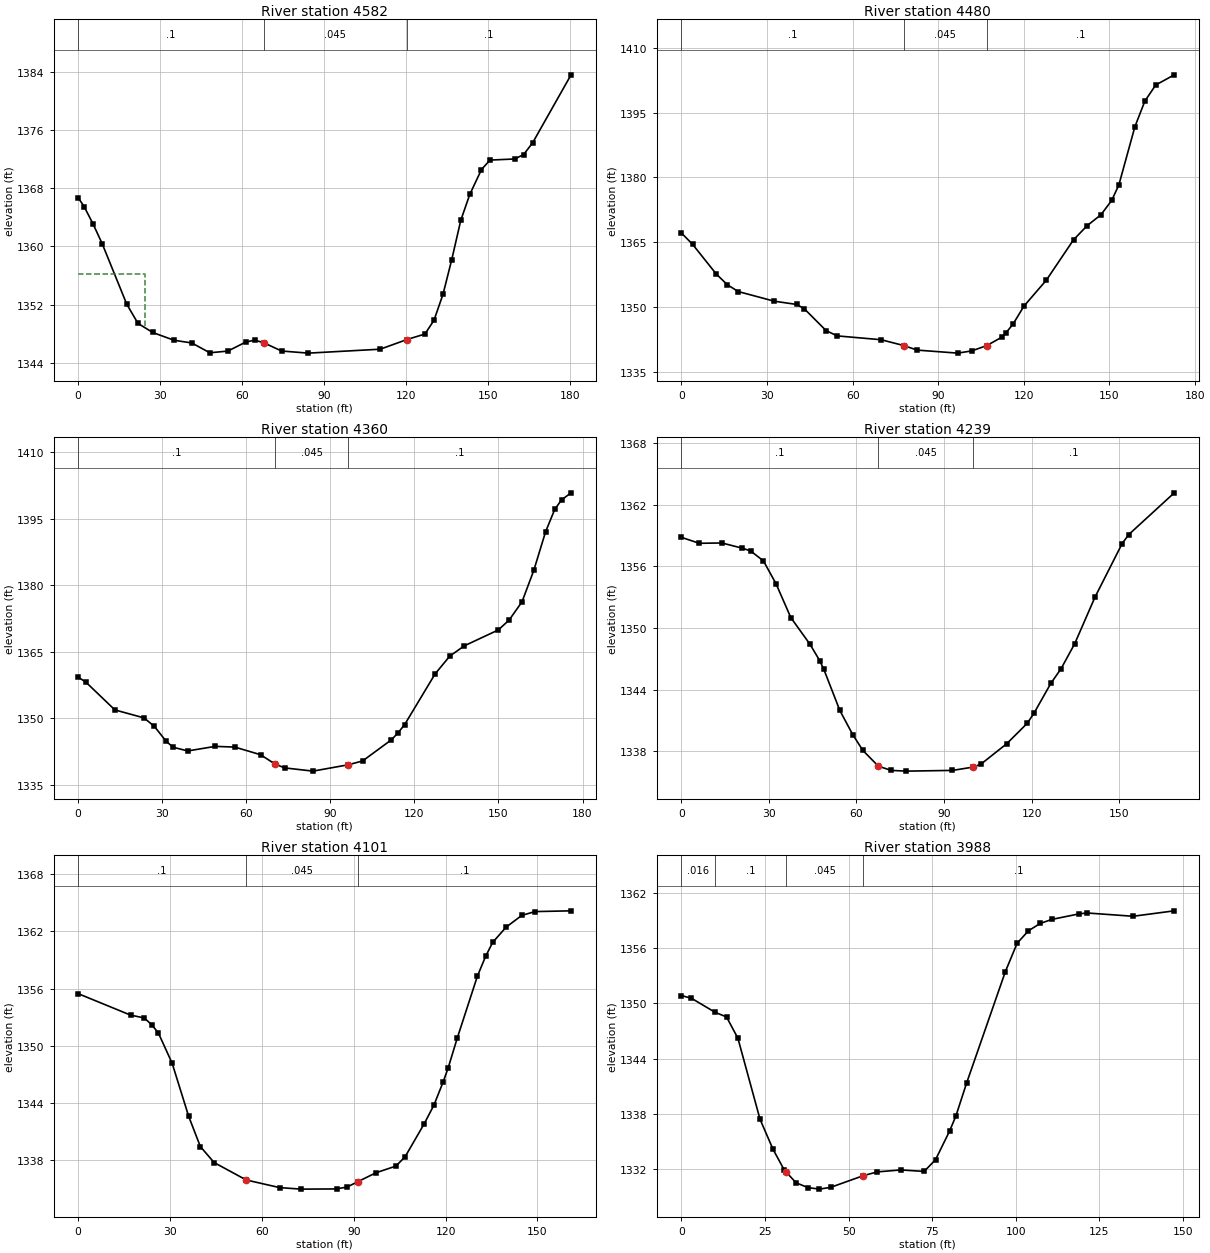
Type RM Length L Ch R = 1 ,4582    ,79.7,102.1,114.2
XS GIS Cut Line= 2
1993008.59676982297372.7358660691993001.94887418297553.068580606
#Sta/Elev= 30
       0 1366.69     2.2 1365.46     5.5 1363.04     8.8 1360.36    17.8 1352.03
    21.9  1349.4    27.3 1348.15    35.1 1347.08    41.6 1346.71    48.2 1345.36
    54.8 1345.59    61.3 1346.82    64.6  1347.1    67.9 1346.75    74.5  1345.6
    84.3 1345.31   110.6 1345.85   120.4 1347.18     127 1347.94   130.3 1349.83
   133.6  1353.4   136.8 1358.16   140.1 1363.56   143.4 1367.14   147.7 1370.57
   150.8 1371.87   159.8 1372.02   163.1 1372.62   166.4 1374.23   180.5  1383.6
#Mann= 3 , 0 , 0
       0      .1       0    67.9    .045       0   120.4      .1       0
#XS Ineff= 2 , 0
           24.54 1356.21
Permanent Ineff=
       F       F
Bank Sta=67.9,120.4
XS Rating Curve= 0 ,0
Exp/Cntr(USF)=0,0
Exp/Cntr=0.3,0.1

Type RM Length L Ch R = 1 ,4480    ,117,120.1,122.9
XS GIS Cut Line= 2
1992957.69238714297357.9787601631992867.37302582297505.199319108
#Sta/Elev= 30
       0 1367.13     3.9 1364.52    12.2 1357.64    16.1 1355.15    19.9 1353.57
    32.5 1351.34    40.4 1350.58      43 1349.62    50.7 1344.53    54.6  1343.3
      70 1342.41      78 1341.05    82.6 1340.01    96.8 1339.31   101.7 1339.82
     107 1341.05   112.3 1343.02   113.6 1343.91   116.2 1346.02     120 1350.17
   127.9 1356.23   137.4 1365.55   142.2 1368.84     147 1371.34   150.8 1374.69
   153.3 1378.29   158.9 1391.73   162.4 1397.67   166.2 1401.39   172.7 1403.75
#Mann= 3 , 0 , 0
       0      .1       0      78    .045       0     107      .1       0
Bank Sta=78,107
XS Rating Curve= 0 ,0
Exp/Cntr(USF)=0,0
Exp/Cntr=0.3,0.1

Type RM Length L Ch R = 1 ,4360    ,119.3,120.8,122.1
XS GIS Cut Line= 2
1992862.85705775297304.6903369861992751.76424333297441.072572574
#Sta/Elev= 30
       0  1359.3     2.8 1358.14    13.1 1351.91    23.5 1350.11    27.2 1348.19
    31.4 1344.84    33.9 1343.49    39.1 1342.66    48.9 1343.69    55.9 1343.53
    65.1 1341.81    70.3 1339.68    73.7 1338.84    83.8 1338.11    96.3 1339.53
   101.5  1340.4   111.8 1345.18   114.2 1346.78   116.5 1348.59   127.4 1360.05
   132.6 1364.03   137.8 1366.36   149.9 1369.93   153.8 1372.17   158.4 1376.29
   162.6 1383.37   166.8 1392.06   170.1 1397.16   172.5 1399.26   175.9 1400.86
#Mann= 3 , 0 , 0
       0      .1       0    70.3    .045       0    96.3      .1       0
Bank Sta=70.3,96.3
XS Rating Curve= 0 ,0
Exp/Cntr(USF)=0,0
Exp/Cntr=0.3,0.1

Type RM Length L Ch R = 1 ,4239    ,135.9,137.4,138.2
XS GIS Cut Line= 2
1992784.27921341297216.1773628961992672.28320538297342.624468739
#Sta/Elev= 30
       0 1358.81     6.1 1358.23    13.9 1358.26    20.9 1357.75    23.7 1357.49
    28.1 1356.52    32.4 1354.31    37.5    1351    44.1 1348.39    47.4 1346.81
    48.8 1345.97    54.3 1341.96    58.7 1339.62    62.2 1338.07    67.5 1336.54
    71.9 1336.13    77.1 1336.06    92.9 1336.13    99.9 1336.45   102.6 1336.73
   111.5 1338.73   118.5 1340.71   120.8 1341.68   126.6  1344.6   130.1 1346.02
   134.8 1348.47   141.7 1352.97     151 1358.18   153.3 1359.08   168.9 1363.14
#Mann= 3 , 0 , 0
       0      .1       0    67.5    .045       0    99.9      .1       0
Bank Sta=67.5,99.9
XS Rating Curve= 0 ,0
Exp/Cntr(USF)=0,0
Exp/Cntr=0.3,0.1

Type RM Length L Ch R = 1 ,4101    ,122,113,100.5
XS GIS Cut Line= 2
1992679.50875428297133.0835504851992567.51274625 297248.69233297
#Sta/Elev= 30
       0 1355.47    17.1 1353.22    21.6 1352.92    24.1 1352.18    26.2 1351.34
    30.7 1348.16    36.1 1342.59    39.9 1339.43    44.4 1337.75    54.9 1335.92
    65.8 1335.12    72.8 1334.96    84.4 1334.98    87.9 1335.19    91.4 1335.75
    97.3 1336.68   103.8 1337.38   106.8 1338.36     113  1341.8   116.2 1343.77
   119.2 1346.19   120.9 1347.72   123.8 1350.78   130.4  1357.3   133.1 1359.39
   135.4 1360.85   139.8 1362.45   144.9 1363.68   149.2 1364.08     161 1364.16
#Mann= 3 , 0 , 0
       0      .1       0    54.9    .045       0    91.4      .1       0
Bank Sta=54.9,91.4
XS Rating Curve= 0 ,0
Exp/Cntr(USF)=0,0
Exp/Cntr=0.3,0.1

Type RM Length L Ch R = 1 ,3988    ,125.4,114.4,104.2
XS GIS Cut Line= 2
 1992550.3520676297083.4079017611992501.57961249297222.499718188
#Sta/Elev= 30
       0 1350.85       3 1350.56      10 1349.05    13.5 1348.53    16.9 1346.22
    23.5 1337.45    27.4 1334.18    30.8 1331.91    31.3 1331.72    34.3 1330.55
    37.8 1330.03    41.3 1329.86    44.7 1330.06    54.4 1331.32    58.6 1331.73
    65.6 1331.94    72.6 1331.78      76 1333.05    80.2 1336.15    82.1  1337.8
    85.3 1341.37    96.9 1353.46   100.4 1356.52   103.8 1357.88   107.3 1358.67
   110.8 1359.11   118.8  1359.7   121.2 1359.81   135.1 1359.45   147.4 1360.04
#Mann= 4 ,-1 , 0
       0    .016       0      10      .1       0    31.3    .045       0
    54.4      .1       0
Bank Sta=31.3,54.4
XS Rating Curve= 0 ,0
Exp/Cntr(USF)=0,0
Exp/Cntr=0.3,0.1

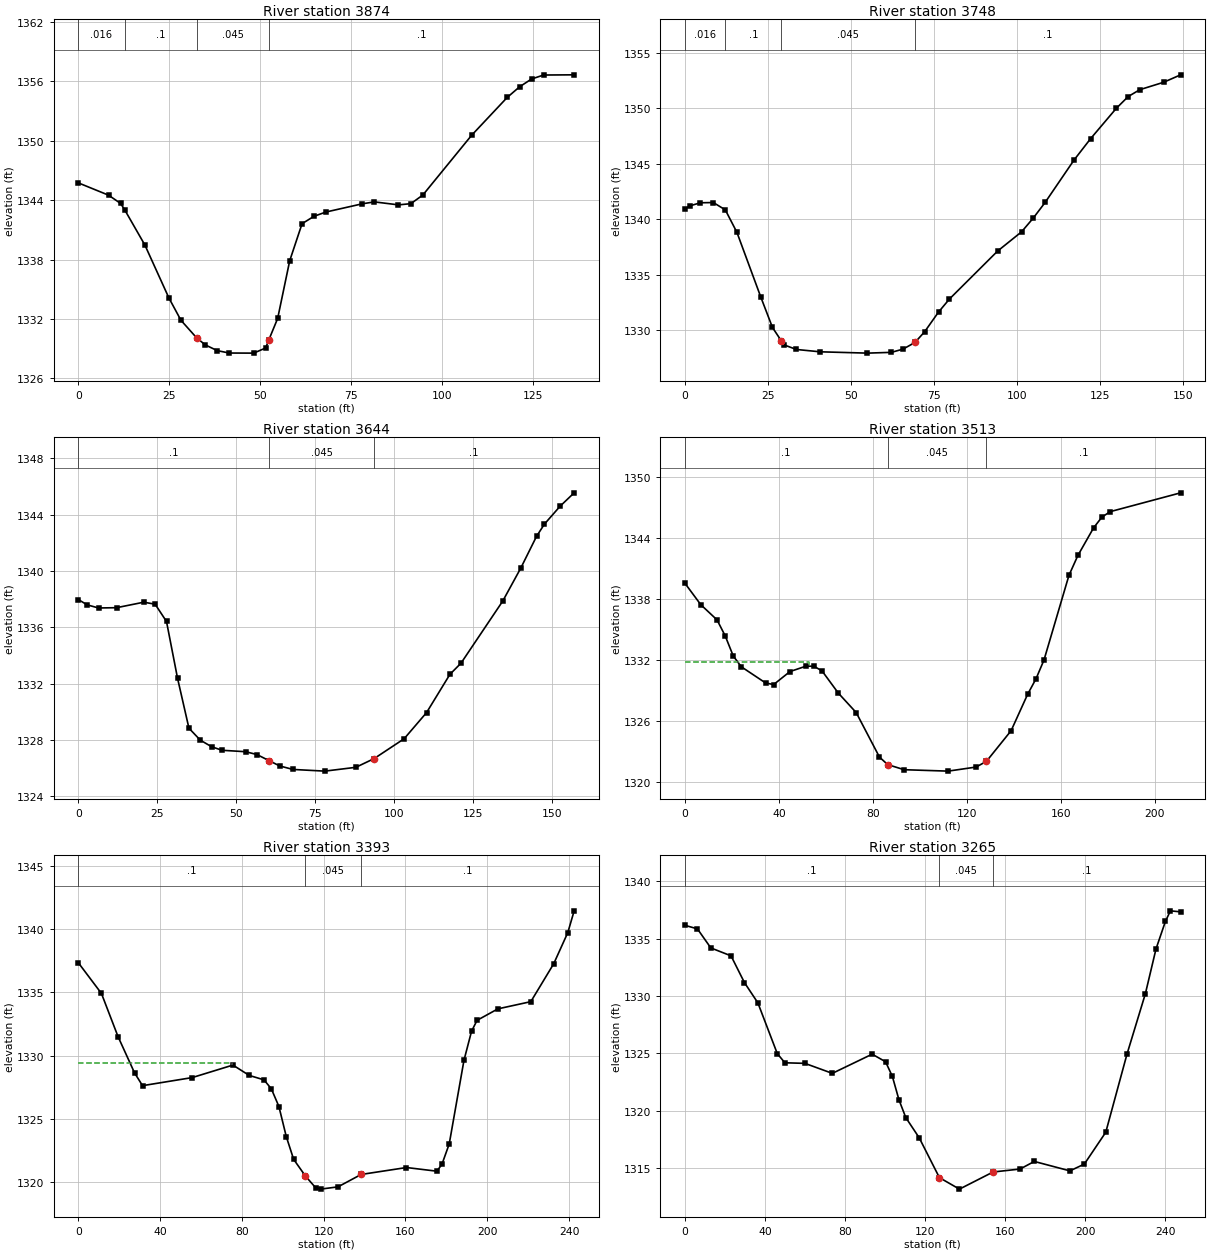
Type RM Length L Ch R = 1 ,3874    ,129.8,125.6,121
XS GIS Cut Line= 2
1992413.96983201297087.9238698271992435.64647873297222.499718188
#Sta/Elev= 30
       0 1345.75     8.3 1344.51    11.6 1343.68    12.7 1343.06    18.3 1339.47
    24.9 1334.13    28.2 1331.88    32.5 1330.11    34.9 1329.39    38.2 1328.81
    41.5 1328.57    48.2 1328.56    51.5 1329.08    52.3 1329.84    54.8 1332.07
    58.1 1337.88    61.5 1341.63    64.8 1342.38    68.1 1342.81    78.1 1343.64
    81.4 1343.83      88 1343.53    91.4 1343.65    94.7 1344.52   108.1 1350.55
   117.9 1354.38   121.3 1355.45   124.6 1356.24   127.9 1356.64   136.3 1356.66
#Mann= 4 ,-1 , 0
       0    .016       0    12.7      .1       0    32.5    .045       0
    52.3      .1       0
Bank Sta=32.5,52.3
XS Rating Curve= 0 ,0
Exp/Cntr(USF)=0,0
Exp/Cntr=0.3,0.1

Type RM Length L Ch R = 1 ,3748    ,103.7,104.5,103.3
XS GIS Cut Line= 2
1992282.10356449297117.7292590611992340.81114934297255.014688262
#Sta/Elev= 30
       0 1340.91     1.5 1341.21     4.7 1341.49     8.6 1341.51    12.2 1340.85
    15.7 1338.82    22.9 1332.98    26.4 1330.25    29.1 1329.03      30 1328.67
    33.6 1328.27    40.7 1328.06      55 1327.94    62.2 1328.01    65.7  1328.3
    69.3  1328.9    72.2 1329.86    76.4 1331.64    79.7 1332.82    94.2 1337.14
   101.4 1338.87   104.9  1340.1   108.5 1341.52   117.2 1345.34   122.2 1347.27
   129.9 1349.99   133.5 1351.06     137 1351.68   144.2 1352.35   149.3 1353.02
#Mann= 4 ,-1 , 0
       0    .016       0    12.2      .1       0    29.1    .045       0
    69.3      .1       0
Bank Sta=29.1,69.3
XS Rating Curve= 0 ,0
Exp/Cntr(USF)=0,0
Exp/Cntr=0.3,0.1

Type RM Length L Ch R = 1 ,3644    ,128.1,131.2,132.8
XS GIS Cut Line= 2
1992183.65546065297149.3410355221992246.87901358297292.948820015
#Sta/Elev= 30
       0 1337.97     2.8 1337.59     6.4 1337.37    12.1 1337.39    20.7 1337.78
    24.3 1337.64    27.9 1336.41    31.4 1332.37      35 1328.83    38.6 1327.98
    42.2 1327.51    45.5 1327.26    52.9 1327.16    56.5 1326.96    60.4 1326.52
    63.7 1326.15    67.9  1325.9      78 1325.78    87.8 1326.05    93.6 1326.67
   103.1 1328.08   110.2 1329.94   117.6 1332.66   121.1 1333.45   134.3 1337.86
     140  1340.2     145 1342.46   147.5 1343.33   152.5 1344.61   156.9 1345.55
#Mann= 3 , 0 , 0
       0      .1       0    60.4    .045       0    93.6      .1       0
Bank Sta=60.4,93.6
XS Rating Curve= 0 ,0
Exp/Cntr(USF)=0,0
Exp/Cntr=0.3,0.1

Type RM Length L Ch R = 1 ,3513    ,100.5,119.6,146
XS GIS Cut Line= 3
1992060.82112926297168.3081013981992080.69138875 297231.53165432
1992131.27023109297367.010696294
#Sta/Elev= 30
       0 1339.54     6.8 1337.42    13.7 1335.93    17.2 1334.35    20.6 1332.39
      24 1331.33    34.4 1329.73    37.8 1329.58    44.7 1330.85    51.6 1331.39
      55 1331.37    58.4 1330.91    65.3 1328.74    72.9 1326.83    82.8 1322.46
    86.3 1321.72    93.3 1321.22     112 1321.08   123.9 1321.48   128.3 1322.04
   138.8 1325.05   145.8 1328.61   149.4 1330.15   152.8    1332   163.4  1340.3
   167.2 1342.25   173.9 1344.97   177.4 1346.01   180.9 1346.55   210.9  1348.4
#Mann= 3 , 0 , 0
       0      .1       0    86.3    .045       0   128.3      .1       0
#XS Ineff= 2 , 0
           52.82 1331.83
Permanent Ineff=
       F       F
Bank Sta=86.3,128.3
XS Rating Curve= 0 ,0
Exp/Cntr(USF)=0,0
Exp/Cntr=0.3,0.1

Type RM Length L Ch R = 1 ,3393    ,110.3,128.4,162
XS GIS Cut Line= 3
1992043.66045061297165.5985205591991995.79118912297233.338041546
1991928.05166813297377.849019652
#Sta/Elev= 30
       0 1337.35    11.3 1334.92    19.4 1331.51    27.5 1328.63    31.4 1327.62
    55.7 1328.26    75.6 1329.25    83.6 1328.43    90.8 1328.08    94.4 1327.37
    98.1 1325.97   101.7 1323.59   105.3 1321.79   111.1 1320.46     116 1319.55
   118.5 1319.43     127 1319.61   138.3 1320.59   160.5 1321.14   175.3 1320.85
   177.8 1321.38   181.4 1323.01   188.6 1329.62   192.3 1331.92     195 1332.79
   205.2  1333.7   221.3 1334.27   232.5 1337.27   239.4 1339.74   242.5 1341.46
#Mann= 3 , 0 , 0
       0      .1       0   111.1    .045       0   138.3      .1       0
#XS Ineff= 2 , 0
           75.21 1329.43
Permanent Ineff=
       F       F
Bank Sta=111.1,138.3
XS Rating Curve= 0 ,0
Exp/Cntr(USF)=0,0
Exp/Cntr=0.3,0.1

Type RM Length L Ch R = 1 ,3265    ,91.2,83.3,73.5
XS GIS Cut Line= 3
1992027.40296558297155.6633908141991864.82811521297190.887941727
1991789.86304531297222.499718188
#Sta/Elev= 30
       0 1336.16     6.3 1335.85      13 1334.19    23.1  1333.5    29.8 1331.17
    36.5 1329.41    46.2 1324.99      50 1324.19      60 1324.14    73.7 1323.27
    93.6 1324.94   100.3 1324.28   103.7    1323     107 1320.96   110.4 1319.42
   117.1 1317.66   127.2 1314.19   137.2 1313.19     154 1314.68   167.5 1314.94
   174.6  1315.6   192.4 1314.78   199.6 1315.37   210.3 1318.14   220.9 1324.94
   230.1 1330.21   235.4  1334.1   240.1  1336.5   242.6 1337.42   247.7 1337.33
#Mann= 3 , 0 , 0
       0      .1       0   127.2    .045       0     154      .1       0
Bank Sta=127.2,154
XS Rating Curve= 0 ,0
Exp/Cntr(USF)=0,0
Exp/Cntr=0.3,0.1

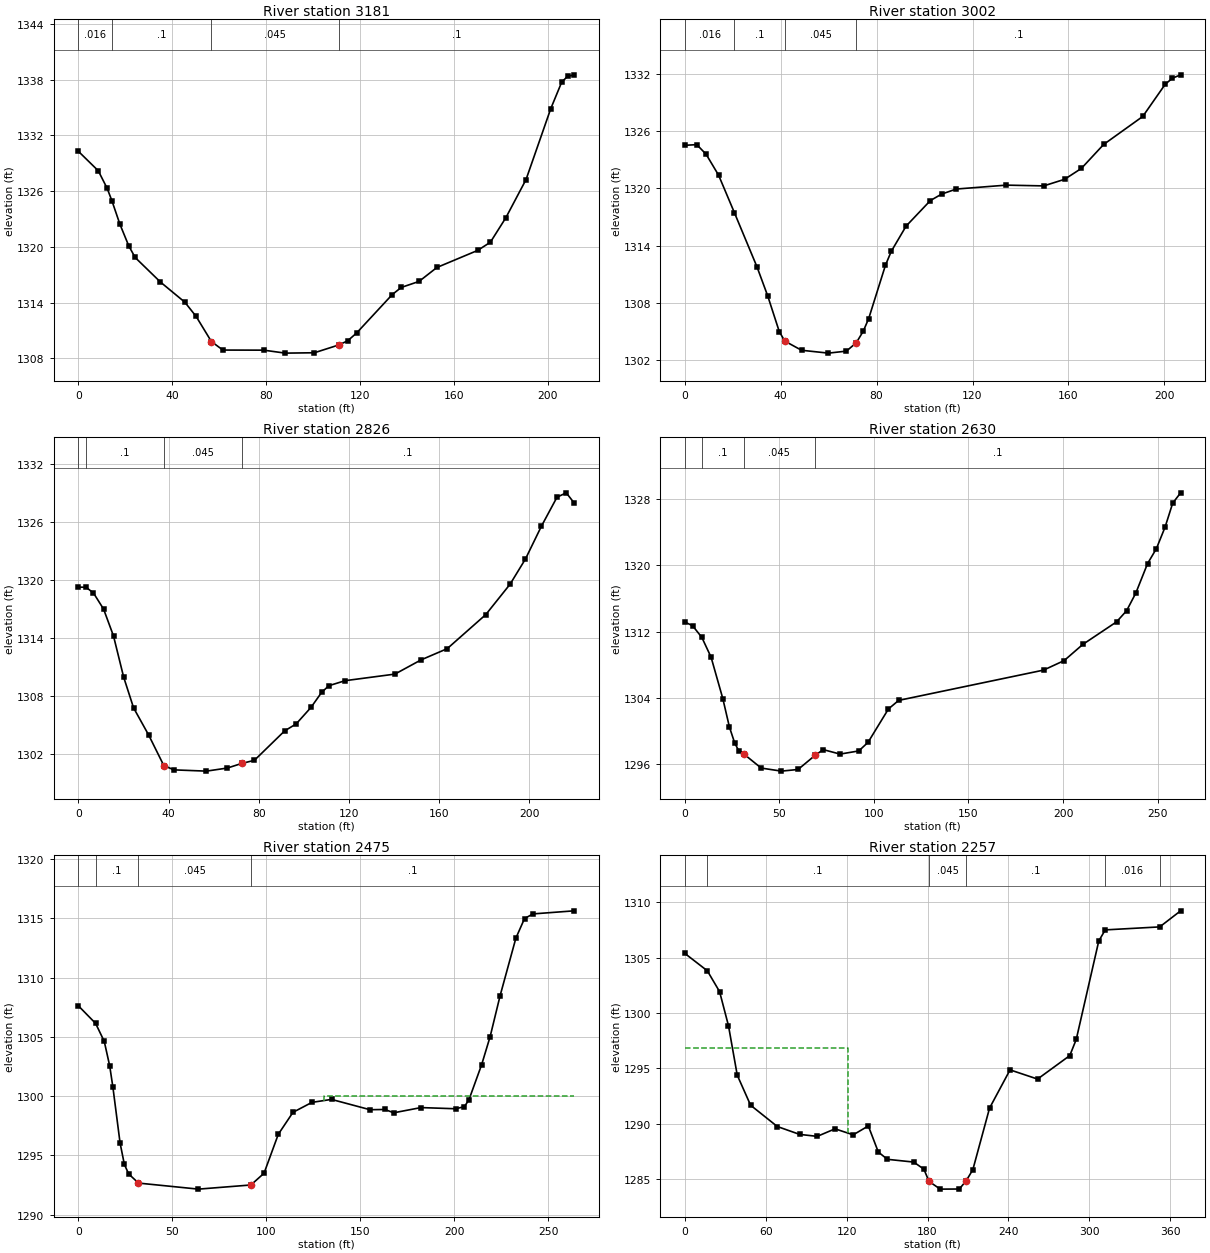
Type RM Length L Ch R = 1 ,3181    ,188.2,179.5,167.7
XS GIS Cut Line= 2
1991923.53570006297070.763191177 1991741.0905902 297177.34003753
#Sta/Elev= 30
       0 1330.28     8.5 1328.18    12.3 1326.28    14.3 1324.96    17.7 1322.44
    21.5 1320.09    24.2 1318.85      35  1316.2    45.4 1314.03    50.2  1312.5
    56.7  1309.8    61.6 1308.88      79 1308.87    88.2 1308.55   100.6 1308.59
     111 1309.43   114.8 1309.88   118.6 1310.72   133.8 1314.86   137.6 1315.62
   145.2 1316.27   152.8 1317.77   170.2 1319.61   175.6 1320.49   182.2 1323.13
   190.8 1327.24   201.3 1334.85     206 1337.73   208.5 1338.35   211.3 1338.51
#Mann= 4 ,-1 , 0
       0    .016       0    14.3      .1       0    56.7    .045       0
     111      .1       0
Bank Sta=56.7,111
XS Rating Curve= 0 ,0
Exp/Cntr(USF)=0,0
Exp/Cntr=0.3,0.1

Type RM Length L Ch R = 1 ,3002    ,174.7,176.5,178.1
XS GIS Cut Line= 2
1991770.89597944296937.9937300421991640.83609914297098.762193185
#Sta/Elev= 30
       0 1324.51       5 1324.58     8.9 1323.57    14.1 1321.38    20.7 1317.45
    30.1 1311.79    34.6 1308.73    39.4 1305.01    41.7 1304.01    48.7 1303.05
    59.9 1302.75    67.4 1302.96    71.5 1303.83    74.4 1305.03    76.7 1306.37
    83.7 1311.96    86.1  1313.4    92.3 1316.05   102.4 1318.72   107.1  1319.4
   113.2 1319.93   134.1 1320.34   149.7 1320.26   158.4 1320.95   165.4 1322.09
   174.7  1324.6     191 1327.53   200.4 1330.91   203.4 1331.54   206.8 1331.89
#Mann= 4 ,-1 , 0
       0    .016       0    20.7      .1       0    41.7    .045       0
    71.5      .1       0
Bank Sta=41.7,71.5
XS Rating Curve= 0 ,0
Exp/Cntr(USF)=0,0
Exp/Cntr=0.3,0.1

Type RM Length L Ch R = 1 ,2826    ,193.4,195.6,200.1
XS GIS Cut Line= 2
1991637.22332469296828.7073028491991488.19637852296990.378959605
#Sta/Elev= 30
       0  1319.3     3.4 1319.29     6.7  1318.7    11.2 1317.03    15.6 1314.25
    20.1    1310    24.5 1306.82    31.2 1304.01    37.9 1300.86    42.4 1300.41
    56.8 1300.28    66.1  1300.6    72.4 1301.07    78.1  1301.4    91.5 1304.44
    96.6 1305.16   103.2 1306.87   107.9 1308.42   111.1 1309.11   118.3 1309.63
   140.4 1310.31     152 1311.78   163.6 1312.94   180.7 1316.46   191.5 1319.61
   198.3 1322.21   205.4 1325.61   212.3  1328.6   216.4 1329.05   219.9    1328
#Mann= 4 ,-1 , 0
       0    .016       0     3.4      .1       0    37.9    .045       0
    72.4      .1       0
Bank Sta=37.9,72.4
XS Rating Curve= 0 ,0
Exp/Cntr(USF)=0,0
Exp/Cntr=0.3,0.1

Type RM Length L Ch R = 1 ,2630    ,155.8,155.2,152.5
XS GIS Cut Line= 2
1991488.19637852296709.4857459111991294.00975169296885.608500478
#Sta/Elev= 30
       0 1313.16     4.1 1312.72       9 1311.31    13.9 1308.91    20.1 1303.91
    23.6 1300.47    26.4 1298.53    28.5 1297.62    31.1 1297.23    40.4 1295.51
    51.1 1295.14    59.9 1295.34    68.8 1297.03    73.2 1297.74    82.1  1297.2
      92 1297.58    96.9 1298.62   107.7 1302.66   113.1 1303.69   189.7 1307.35
   200.6  1308.5   210.5 1310.46   228.3 1313.18   233.6 1314.52   238.5 1316.66
   244.7 1320.22   249.4 1322.04     254 1324.65     258 1327.53   262.2 1328.78
#Mann= 4 ,-1 , 0
       0    .016       0       9      .1       0    31.1    .045       0
    68.8      .1       0
Bank Sta=31.1,68.8
XS Rating Curve= 0 ,0
Exp/Cntr(USF)=0,0
Exp/Cntr=0.3,0.1

Type RM Length L Ch R = 1 ,2475    ,198.6,217.6,214.5
XS GIS Cut Line= 2
 1991363.5556599296613.7472229161991180.20735643 296803.41788168
#Sta/Elev= 30
       0 1307.63     9.2 1306.14    13.8 1304.62    16.7 1302.55    18.4 1300.75
    22.2 1296.06    24.5 1294.24    26.8 1293.44      32 1292.67    63.9 1292.16
    91.8 1292.51    98.8  1293.5   106.4 1296.79   114.2 1298.64   124.3 1299.48
   134.7 1299.73   155.2 1298.86   163.1 1298.88   167.8  1298.6   182.3 1299.04
   200.8 1298.94   205.4 1299.12   207.8 1299.69   214.6 1302.67   219.1 1305.03
   224.4 1308.48   232.8 1313.34   237.4 1314.99   241.9 1315.38   263.8 1315.64
#Mann= 4 ,-1 , 0
       0    .016       0     9.2      .1       0      32    .045       0
    91.8      .1       0
#XS Ineff= 2 , 0
                          130.82         1299.99
Permanent Ineff=
       F       F
Bank Sta=32,91.8
XS Rating Curve= 0 ,0
Exp/Cntr(USF)=0,0
Exp/Cntr=0.3,0.1

Type RM Length L Ch R = 1 ,2257    ,147.4,166.4,187.1
XS GIS Cut Line= 4
1991302.13849421296568.5875422581991180.20735643  296557.7492189
1991083.56563982296611.0376420771990967.95685734 296680.58355029
#Sta/Elev= 30
       0 1305.38    16.7 1303.81    25.8 1301.93    32.4 1298.85    38.9 1294.39
    48.8 1291.68    68.6 1289.76    85.1 1289.05    98.2 1288.87   111.4 1289.55
   124.9 1289.01   136.1 1289.81   143.5 1287.46   150.2  1286.8   169.8 1286.55
   177.3 1285.91   181.1 1284.81   189.4 1284.11   203.6 1284.12   208.7 1284.87
   213.6 1285.86     226 1291.42   241.2 1294.87   261.6 1294.04   285.5 1296.16
   290.3 1297.62     307  1306.5   311.8  1307.5   352.2 1307.77   367.7 1309.22
#Mann= 6 ,-1 , 0
       0    .016       0    16.7      .1       0   181.1    .045       0
   208.7      .1       0   311.8    .016       0   352.2      .1       0
#XS Ineff= 2 , 0
          121.01 1296.88
Permanent Ineff=
       F       F
Bank Sta=181.1,208.7
XS Rating Curve= 0 ,0
Exp/Cntr(USF)=0,0
Exp/Cntr=0.5,0.3