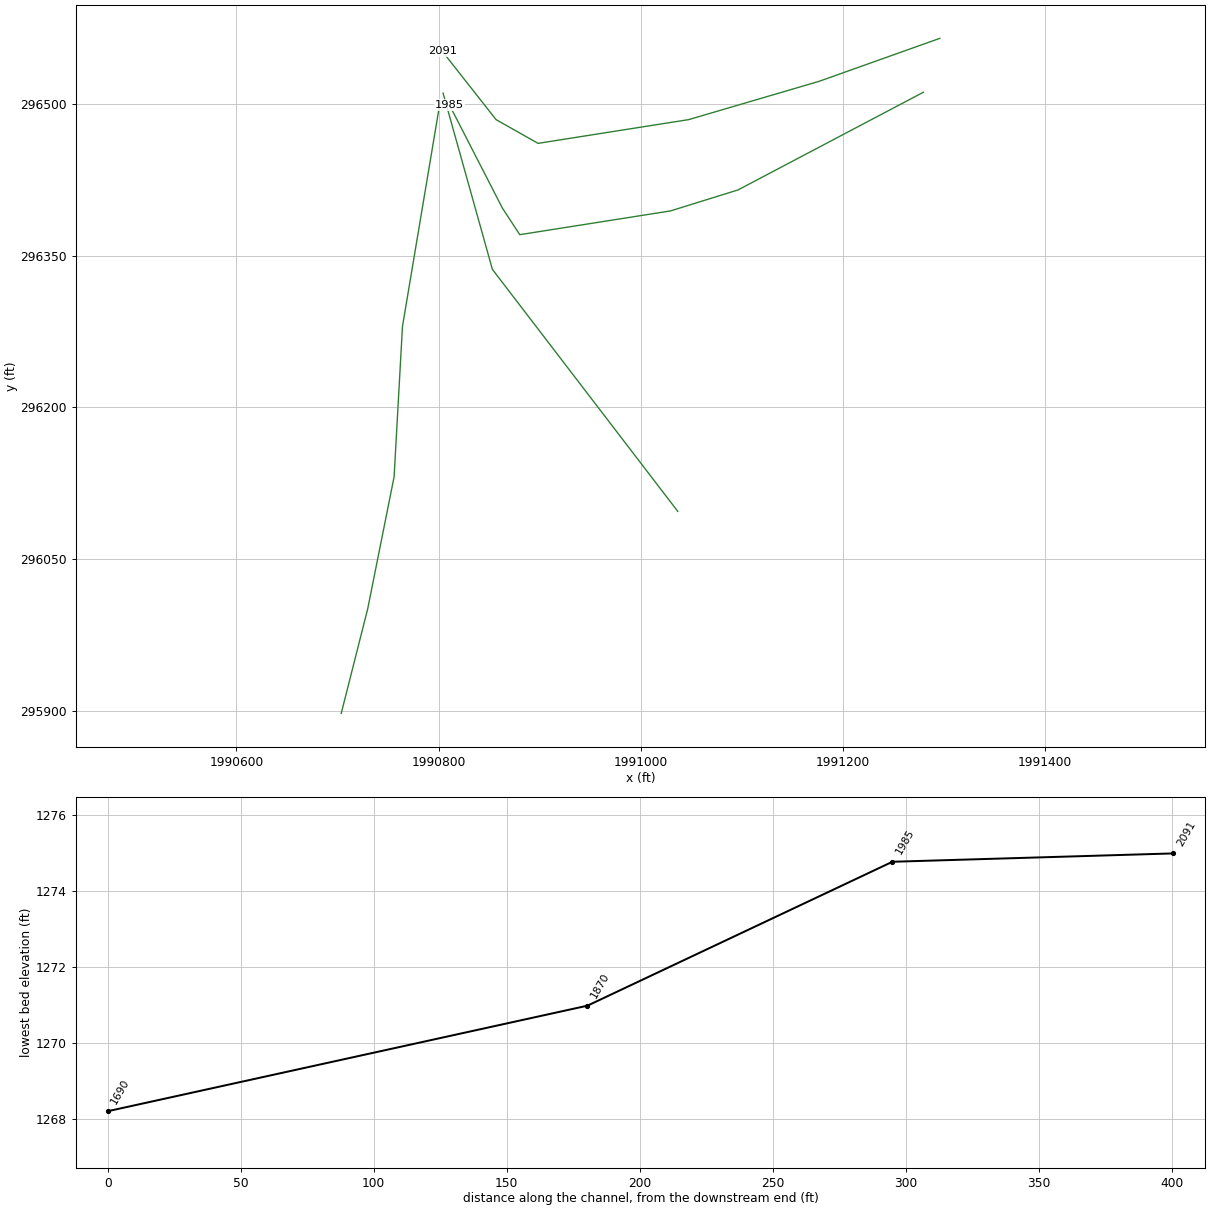
HEC-RAS study MEADOWCK_AE.prj: MEADOWCK_AE

--- MEADOWCK_AE.g01 (geometry) --- (continued)

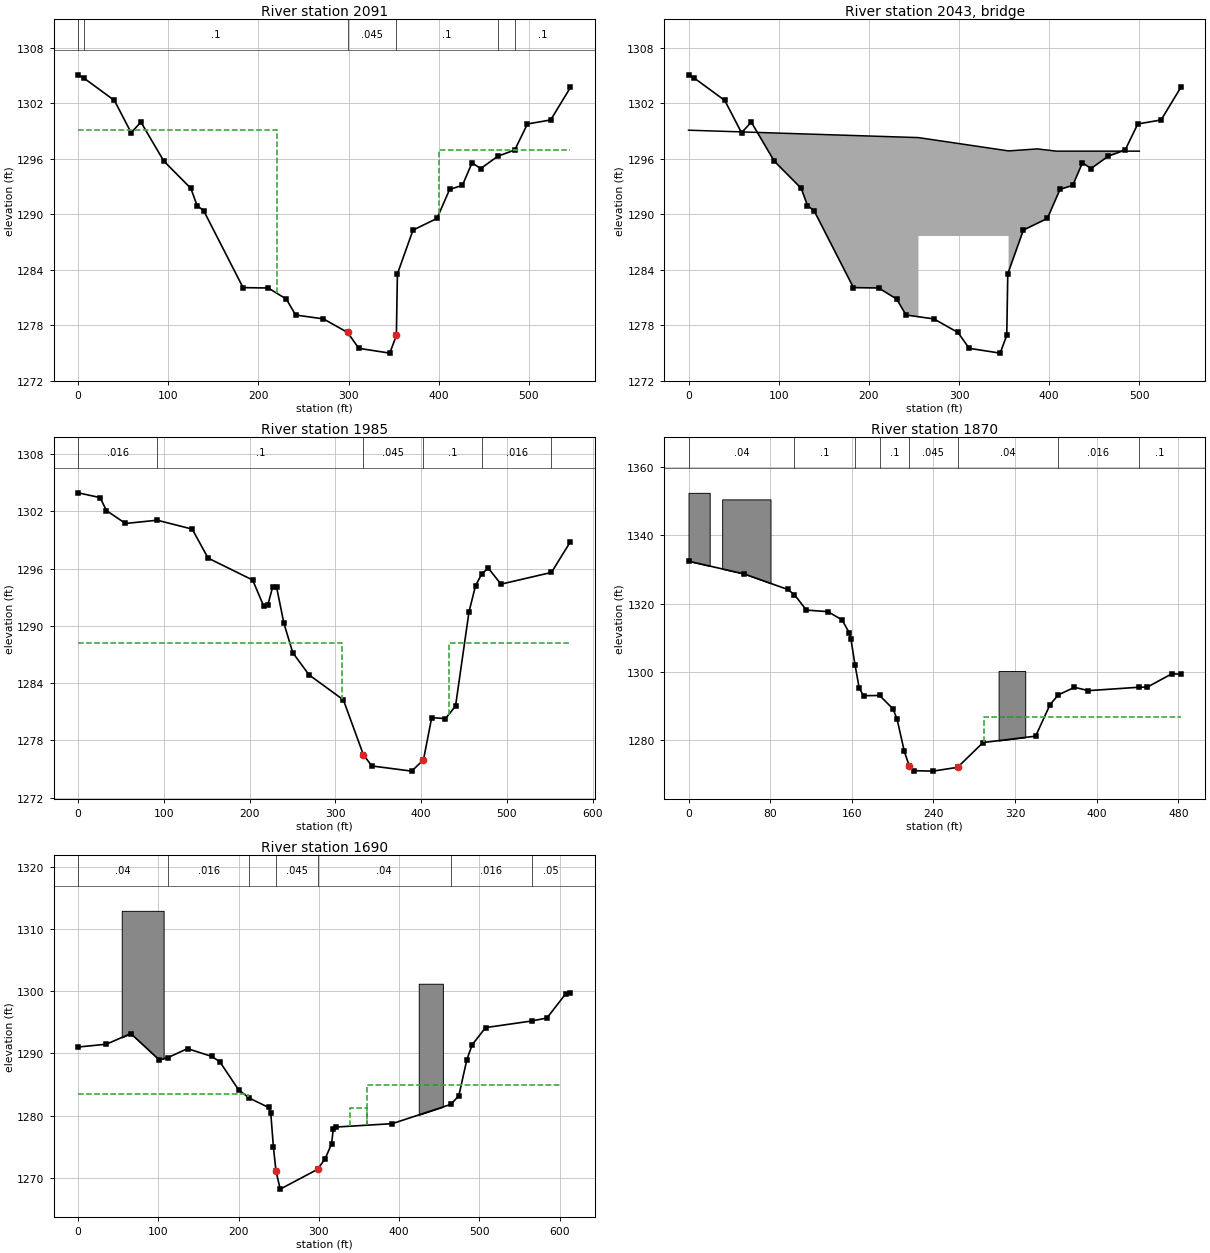
Type RM Length L Ch R = 1 ,2091    ,114.4,105.6,114.3
BEGIN DESCRIPTION:
Channel burned from survey: 54089MEC032BU
END DESCRIPTION:
XS GIS Cut Line= 6
1991295.81613891296564.9747678051991176.59458198296522.524667986
1991047.43789529296484.5905362341990898.41094912296461.107502291
1990856.86404292296484.5905362341990803.57561974296552.330057221
#Sta/Elev= 30
       0 1305.07     6.6  1304.7    40.2  1302.3    58.8 1298.81    69.6 1299.96
      95 1295.75     125  1292.8   131.9 1290.94   139.2 1290.39   182.9 1282.07
   210.9 1282.03   230.9 1280.83   241.2 1279.11   272.1 1278.69   298.9 1277.22
  311.24 1275.51  345.61 1274.99  352.95  1276.9   354.1 1283.56   371.4 1288.29
     398 1289.55     412 1292.68   426.2 1293.13   436.9 1295.56   446.5 1294.94
   465.4 1296.27   484.3 1296.95   498.3 1299.76   524.1 1300.19     546 1303.71
#Mann= 6 ,-1 , 0
       0    .016       0     6.6      .1       0   298.9    .045       0
  352.95      .1       0   465.4    .016       0   484.3      .1       0
#XS Ineff= 2 ,-1
       0     220 1299.09     400545.9612 1296.91
Permanent Ineff=
       F       F
Bank Sta=298.9,352.95
XS Rating Curve= 0 ,0
Exp/Cntr(USF)=0,0
Exp/Cntr=0.5,0.3

Type RM Length L Ch R = 3 ,2043    ,,,
BEGIN DESCRIPTION:
CSX Railroad
Bridge Survey Number: 54089MEC030
END DESCRIPTION:
Bridge Culvert--1,0,-1,-1, 0
Deck Dist Width WeirC Skew NumUp NumDn MinLoCord MaxHiCord MaxSubmerge Is_Ogee
40,20,2.6,0, 8, 8, , , 0.98, 0, 0,0,,
       0     255     255     355     355     387     408     500
1299.0851298.2861298.2861296.8471296.8471297.0641296.8211296.821
                 1287.65 1287.65
       0     267     280     320     320     420     420     600
1299.0851299.0851298.7111298.4061298.406 1297.04    12971296.821
                                 1287.65 1287.65
BR Coef=-1 , 1 , 0 ,, 0 ,,,0.8,0,1.2,0,
WSPro=,,,, 1 ,,,, 0 ,,,, 0 ,,,,-1 ,-1 ,-1 , 0 , 0 , 0 , 0 , 0
BR U #Sta/Elev= 30
       0 1305.07     6.6  1304.7    40.2  1302.3    58.8 1298.81    69.6 1299.96
      95 1295.75     125  1292.8   131.9 1290.94   139.2 1290.39   182.9 1282.07
   210.9 1282.03   230.9 1280.83   241.2 1279.11   272.1 1278.69   298.9 1277.22
  311.24 1275.51  345.61 1274.99  352.95  1276.9   354.1 1283.56   371.4 1288.29
     398 1289.55     412 1292.68   426.2 1293.13   436.9 1295.56   446.5 1294.94
   465.4 1296.27   484.3 1296.95   498.3 1299.76   524.1 1300.19     546 1303.71
BR U #Mann= 6
       0    .016     6.6      .1   298.9     .04  352.95      .1   465.4    .016
   484.3      .1
BR D #Sta/Elev= 30
       0 1303.93    25.6 1303.43      33 1302.07    55.2 1300.72    92.2 1301.06
     133 1300.13   151.6 1297.09   203.6 1294.79   216.4 1292.06   221.2 1292.16
   226.8 1294.05   231.5 1294.03   239.9  1290.3   250.3 1287.18   269.3 1284.86
   309.4 1282.23   332.7 1276.48   342.6 1275.31   389.1 1274.77   402.8 1275.96
   412.4 1280.38   428.4 1280.27   440.2 1281.59   455.9 1291.46   463.5  1294.2
   470.9 1295.45   478.4 1296.04   493.2 1294.36   552.1 1295.59   574.2 1298.81
BR D #Mann= 6
       0    .016    92.2      .1   332.7     .04   402.8      .1   470.9    .016
   552.1      .1
BC Design=,, 0 ,, 0 ,,,,,,
BC Use User HTab Curves=0
BC User HTab FreeFlow(D)= 0

Type RM Length L Ch R = 1 ,1985    ,142.5,114.6,68.2
XS GIS Cut Line= 6
1991279.55865388296511.686344629 1991096.2103504 296415.04462802
1991029.37402303296394.2711749171990880.34707686296370.788140975
1990863.18639821296396.9807557571990810.80116865296499.041634044
#Sta/Elev= 30
       0 1303.93    25.6 1303.43      33 1302.07    55.2 1300.72    92.2 1301.06
     133 1300.13   151.6 1297.09   203.6 1294.79   216.4 1292.06   221.2 1292.16
   226.8 1294.05   231.5 1294.03   239.9  1290.3   250.3 1287.18   269.3 1284.86
   309.4 1282.23   332.7 1276.48   342.6 1275.31   389.1 1274.77   402.8 1275.96
   412.4 1280.38   428.4 1280.27   440.2 1281.59   455.9 1291.46   463.5  1294.2
   470.9 1295.45   478.4 1296.04   493.2 1294.36   552.1 1295.59   574.2 1298.81
#Mann= 6 ,-1 , 0
       0    .016       0    92.2      .1       0   332.7    .045       0
   402.8      .1       0   470.9    .016       0   552.1      .1       0
#XS Ineff= 2 ,-1
       0     308 1288.23     432574.1688 1288.23
Permanent Ineff=
       F       F
Bank Sta=332.7,402.8
XS Rating Curve= 0 ,0
Exp/Cntr(USF)=0,0
Exp/Cntr=0.5,0.3

Type RM Length L Ch R = 1 ,1870    ,203.3,180.3,159.5
XS GIS Cut Line= 3
1991036.59957194296097.1204761861990853.25126846296336.466783675
1990804.47881335296510.783151015
#Sta/Elev= 30
       0 1332.41    54.7 1328.66    97.1 1324.15   103.8 1322.62   115.5  1318.1
   136.6 1317.64   150.4 1315.26   157.7 1311.36   159.1 1309.71   163.2 1302.05
   167.3 1295.26   171.5 1293.05   187.3 1293.11   200.4  1289.2   204.4 1286.18
   211.5 1276.75   216.2 1272.62   221.1 1271.11   239.6 1270.98   263.7 1272.09
   288.7 1279.35   340.2 1281.21   354.4 1290.47   362.4 1293.28   378.3  1295.5
   391.9 1294.53   441.2 1295.52   449.8 1295.58   473.7 1299.46   482.5 1299.32
#Mann= 8 ,-1 , 0
       0     .04       0   103.8      .1       0   163.2    .016       0
   187.3      .1       0   216.2    .045       0   263.7     .04       0
   362.4    .016       0   441.2      .1       0
#XS Ineff= 2 , 0
                          289.58         1286.76
Permanent Ineff=
       F       F
#Block Obstruct= 3 ,-1
       0   20.74 1352.41   32.97   80.35 1350.49  303.92     330 1300.26
Bank Sta=216.2,263.7
XS Rating Curve= 0 ,0
Exp/Cntr(USF)=0,0
Exp/Cntr=0.5,0.3

Type RM Length L Ch R = 1 ,1690    ,73.5,74.8,71.6
BEGIN DESCRIPTION:
Channel burned from survey:54089MEC022BU
END DESCRIPTION:
XS GIS Cut Line= 5
1990703.74114788295897.3321318511990729.89673186296000.577858093
1990756.05231584296131.3557779991990764.31197394296280.029623788
1990801.48043539296501.663782787
#Sta/Elev= 30
       0 1291.04    35.1 1291.49    65.6  1293.2   101.1 1288.97     112 1289.35
   136.3 1290.78   166.5 1289.53   176.5 1288.68   199.9 1284.17   213.3 1282.83
   237.5 1281.32   240.1 1280.36   243.3 1274.99   246.6 1271.06   251.8  1268.2
  298.41 1271.38  307.88 1273.11  315.82 1275.46   317.9 1277.82   321.4 1278.18
   391.3 1278.72   464.4 1281.82   474.4  1283.2   484.4    1289     491 1291.39
   507.7 1294.16     565 1295.22   584.2  1295.7   607.5 1299.57   613.5 1299.74
#Mann= 7 ,-1 , 0
       0     .04       0     112    .016       0   213.3     .08       0
   246.6    .045       0  298.41     .04       0   464.4    .016       0
     565     .05       0
#XS Ineff= 3 ,-1
       0   211.5 1283.46   338.5     360 1281.17     360     600    1285
Permanent Ineff=
       F       F       F
#Block Obstruct= 2 ,-1
   54.32  106.51 1312.93  424.47  454.53 1301.21
Bank Sta=246.6,298.41
XS Rating Curve= 0 ,0
Exp/Cntr(USF)=0,0
Exp/Cntr=0.5,0.3