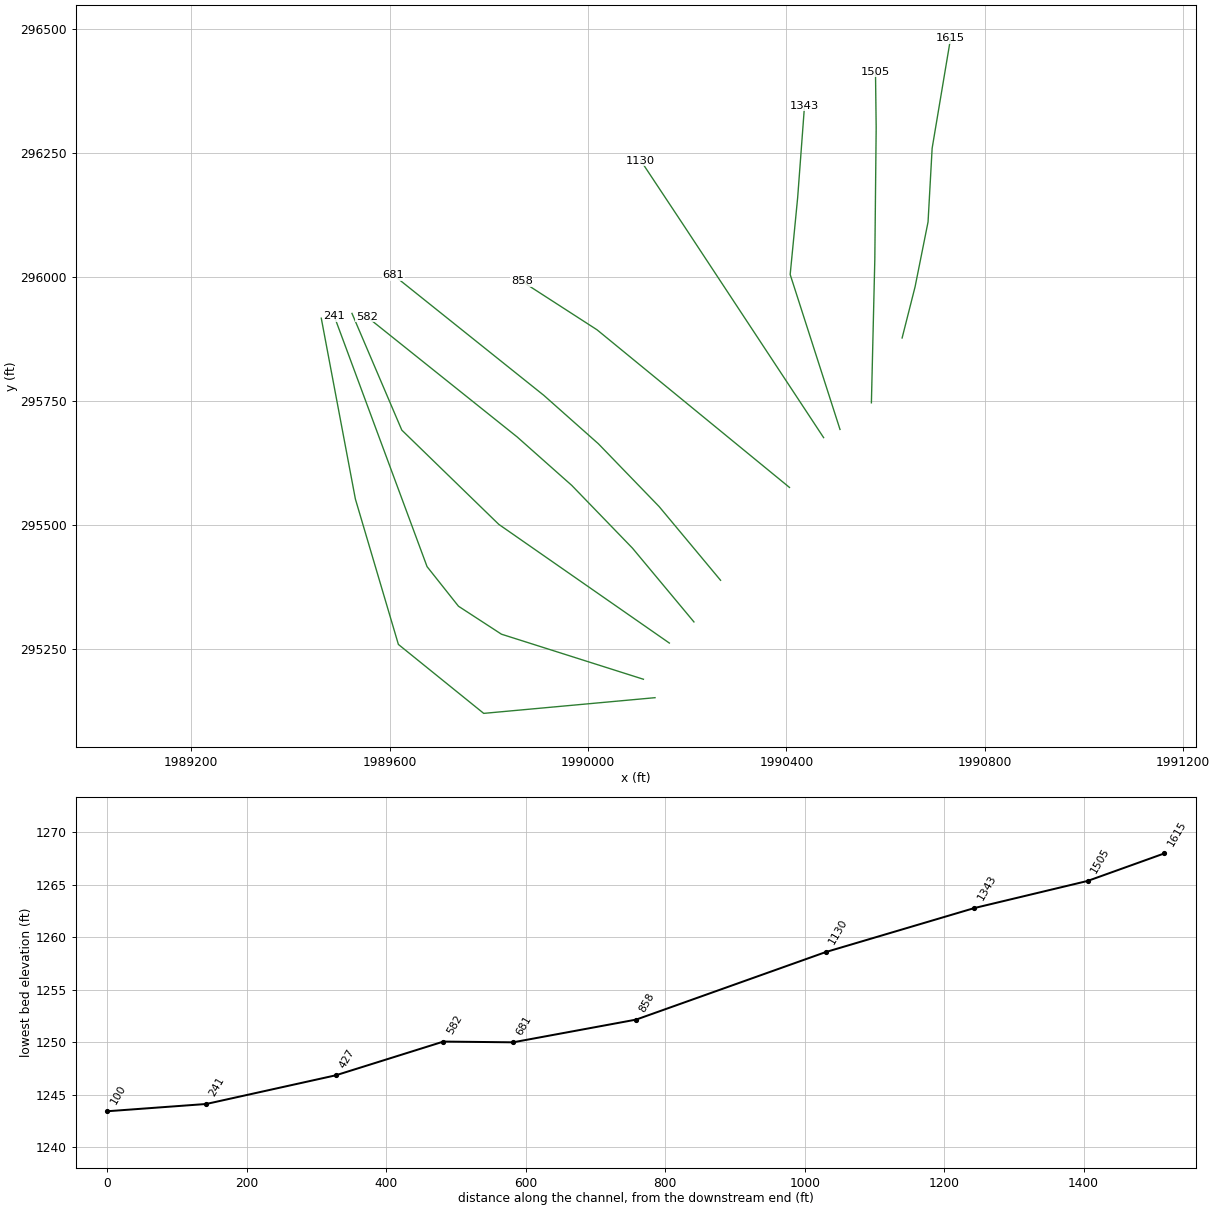
HEC-RAS study MEADOWCK_AE.prj: MEADOWCK_AE

--- MEADOWCK_AE.g01 (geometry) --- (continued)

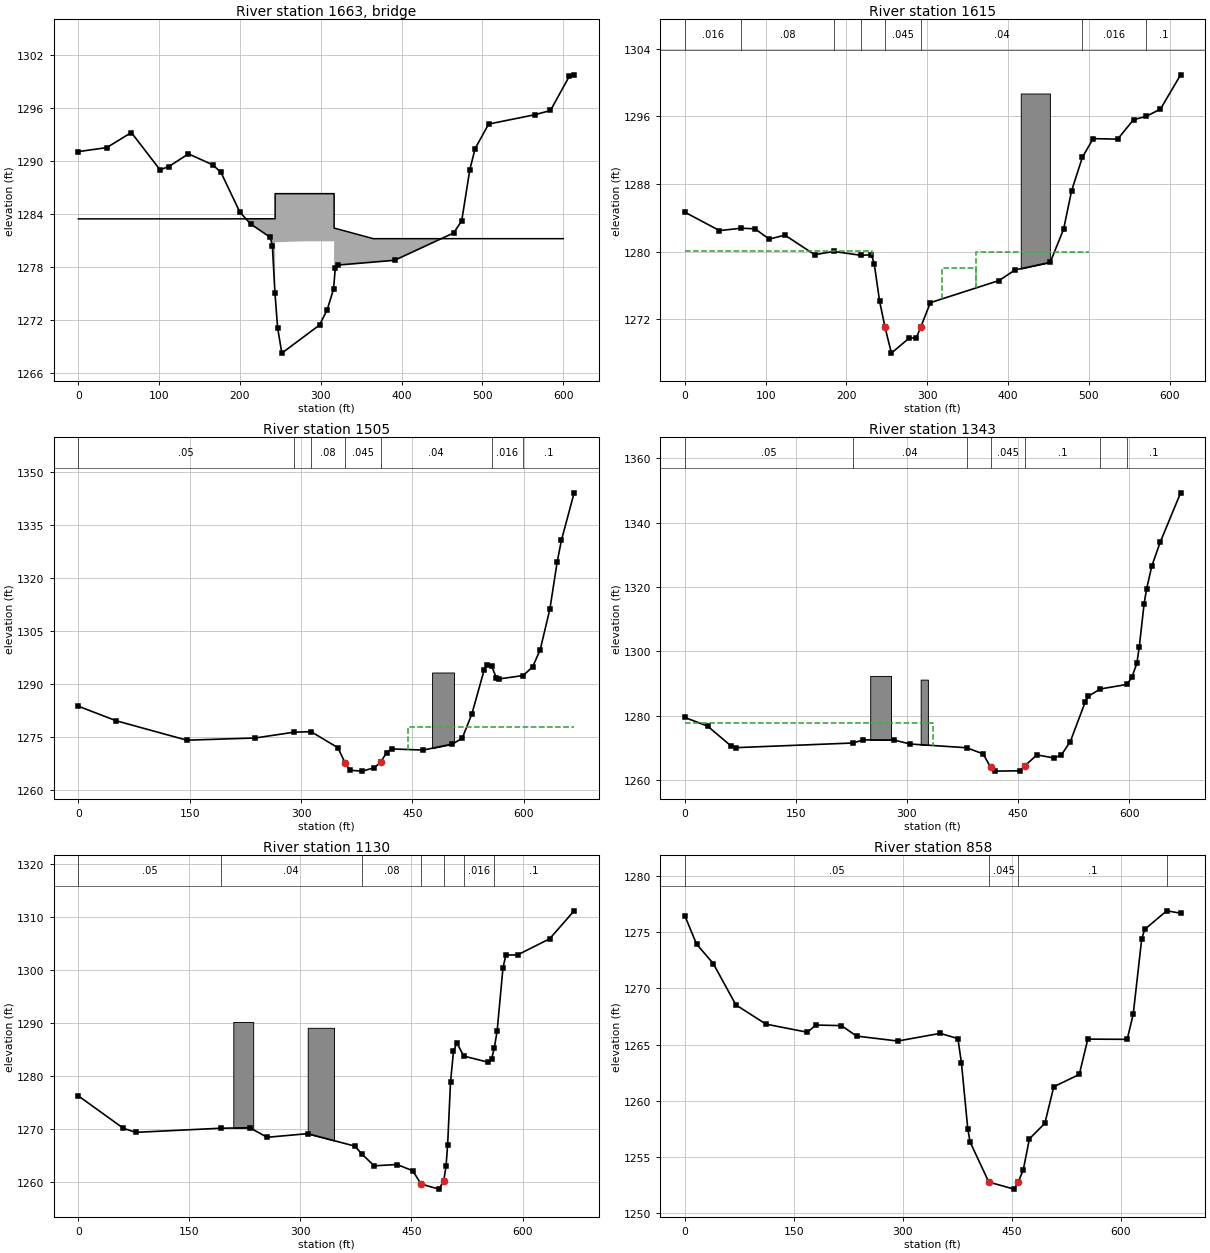
Type RM Length L Ch R = 3 ,1663    ,,,
BEGIN DESCRIPTION:
Claypool Road
Bridge Survey Number: 54089MEC020
Included railing with height of 2.7
END DESCRIPTION:
Bridge Culvert--1,0,-1,-1, 0
Deck Dist Width WeirC Skew NumUp NumDn MinLoCord MaxHiCord MaxSubmerge Is_Ogee
27,24,2.6,0, 9, 9, , , 0.98, 0, 0,0,,
       0     187   243.5   243.5     280   316.5   316.5     365     600
1283.4181283.4181283.4291286.2721286.2721286.2721282.3741281.1721281.172
                        1280.7581280.8721280.872
       0     187   238.5   238.5     275   311.5   311.5     365     600
1283.4181283.418  1283.41286.2721286.2721286.272 1282.461281.1721281.172
                        1280.7581280.8721280.872
BR Coef=-1 , 1 , 0 ,, 0 ,,,0.8,0,1.2,0,
WSPro=,,,, 1 ,,,, 0 ,,,, 0 ,,,,-1 ,-1 ,-1 , 0 , 0 , 0 , 0 , 0
BR U #Sta/Elev= 30
       0 1291.04    35.1 1291.49    65.6  1293.2   101.1 1288.97     112 1289.35
   136.3 1290.78   166.5 1289.53   176.5 1288.68   199.9 1284.17   213.3 1282.83
   237.5 1281.32   240.1 1280.36   243.3 1274.99   246.6 1271.06   251.8  1268.2
  298.41 1271.38  307.88 1273.11  315.82 1275.46   317.9 1277.82   321.4 1278.18
   391.3 1278.72   464.4 1281.82   474.4  1283.2   484.4    1289     491 1291.39
   507.7 1294.16     565 1295.22   584.2  1295.7   607.5 1299.57   613.5 1299.74
BR U #Mann= 7
       0     .04     112    .016   213.3     .08   246.6     .04  298.41     .04
   464.4    .016     565     .05
BR D #Sta/Elev= 30
       0 1284.66    42.9 1282.48      70 1282.76    86.9 1282.69   104.4 1281.47
   123.9 1281.94   160.7 1279.63   184.2 1280.01   217.6 1279.56     231 1279.61
   234.4 1278.55     241 1274.14   247.6  1271.1  255.61 1267.98  278.02 1269.79
   286.4 1269.77  292.11 1271.11  303.82 1273.95   388.8 1276.57   408.8 1277.83
   452.1 1278.72   468.7 1282.64   478.6 1287.19     492 1291.17   505.3 1293.36
   535.6  1293.3   555.2  1295.6   570.7 1295.99   588.5 1296.85   613.5 1300.91
BR D #Mann= 8
       0    .016      70     .08   184.2    .016   217.6     .08   247.6     .04
  292.11     .04     492    .016   570.7      .1
BC Design=,, 0 ,, 0 ,,,,,,
BC Use User HTab Curves=0
BC User HTab FreeFlow(D)= 0

Type RM Length L Ch R = 1 ,1615    ,108.3,110,110.9
BEGIN DESCRIPTION:
Channel burn from survey: 54089MEC018BD
END DESCRIPTION:
XS GIS Cut Line= 5
1990633.53405403295876.6829866031990659.68963801295979.928712845
  1990685.845222296110.706632751 1990694.1048801296259.380478539
1990731.27334154296481.014637538
#Sta/Elev= 30
       0 1284.66    42.9 1282.48      70 1282.76    86.9 1282.69   104.4 1281.47
   123.9 1281.94   160.7 1279.63   184.2 1280.01   217.6 1279.56     231 1279.61
   234.4 1278.55     241 1274.14   247.6  1271.1  255.61 1267.98  278.02 1269.79
   286.4 1269.77  292.11 1271.11  303.82 1273.95   388.8 1276.57   408.8 1277.83
   452.1 1278.72   468.7 1282.64   478.6 1287.19     492 1291.17   505.3 1293.36
   535.6  1293.3   555.2  1295.6   570.7 1295.99   588.5 1296.85   613.5 1300.91
#Mann= 8 ,-1 , 0
       0    .016       0      70     .08       0   184.2    .016       0
   217.6     .08       0   247.6    .045       0  292.11     .04       0
     492    .016       0   570.7      .1       0
#XS Ineff= 3 ,-1
       0 231.167 1280.07 318.833     360    1278     360     500    1280
Permanent Ineff=
       F       F       F
#Block Obstruct= 1 ,-1
   415.7  451.74  1298.7
Bank Sta=247.6,292.11
XS Rating Curve= 0 ,0
Exp/Cntr(USF)=0,0
Exp/Cntr=0.5,0.3

Type RM Length L Ch R = 1 ,1505    ,164.6,162.4,157.3
XS GIS Cut Line= 4
1990571.58661829295745.905066697 1990578.4696667296034.993100174
1990581.22288607296300.6787690361990579.84627639 296413.56076306
#Sta/Elev= 30
       0 1283.76      51 1279.63   146.2 1274.13   238.1 1274.75   290.6  1276.4
   313.5 1276.54   349.6 1271.99   359.5 1267.58     366 1265.61   382.4 1265.36
   398.8 1266.33   407.4 1267.95   415.2 1270.63   421.8 1271.65   464.5 1271.33
   503.8 1273.03     517 1274.67   530.1  1281.6   546.5 1293.97     550  1295.5
   556.6 1295.13   562.9 1291.88   566.2 1291.47     599 1292.45   611.7 1294.84
     622 1299.72   635.1 1311.28   644.9  1324.6   650.6 1330.75   667.8 1344.23
#Mann= 7 ,-1 , 0
       0     .05       0   290.6    .016       0   313.5     .08       0
   359.5    .045       0   407.4     .04       0   556.6    .016       0
     599      .1       0
#XS Ineff= 1 ,-1
  444.45667.7603 1277.96
Permanent Ineff=
       F
#Block Obstruct= 1 ,-1
  476.45  505.95 1293.31
Bank Sta=359.5,407.4
XS Rating Curve= 0 ,0
Exp/Cntr(USF)=0,0
Exp/Cntr=0.3,0.1

Type RM Length L Ch R = 1 ,1343    ,180,213.2,234.3
XS GIS Cut Line= 4
1990508.26257286295692.2172890511990407.77006598296004.707687143
 1990422.9127725296160.2645813471990436.67886933296344.730278899
#Sta/Elev= 30
       0 1279.45    30.7 1276.78    61.9  1270.7    68.6 1270.07   227.1 1271.52
   240.9 1272.49   282.3 1272.44   304.5  1271.2   380.6 1270.05   402.9 1268.13
   412.8 1264.03   419.4 1262.78   452.4 1262.89   459.3 1264.46   475.5 1267.83
   498.5 1266.86   508.4 1267.79   520.4 1271.89   540.9  1284.4   544.6 1286.01
     561  1288.3   597.2 1289.73   603.8 1292.02   610.4 1296.27   613.7 1301.49
   620.2 1314.76   623.5 1319.35   630.6 1326.51   641.9 1333.89   669.5 1349.25
#Mann= 7 ,-1 , 0
       0     .05       0   227.1     .04       0   380.6     .08       0
   412.8    .045       0   459.3      .1       0     561    .016       0
   597.2      .1       0
#XS Ineff= 2 , 0
          334.82 1277.84
Permanent Ineff=
       F       F
#Block Obstruct= 2 ,-1
  250.37  278.46 1292.36  318.51  328.25 1291.21
Bank Sta=412.8,459.3
XS Rating Curve= 0 ,0
Exp/Cntr(USF)=0,0
Exp/Cntr=0.3,0.1

Type RM Length L Ch R = 1 ,1130    ,242.1,272,270.2
XS GIS Cut Line= 3
1990475.22394046295675.697972852 1990193.0189554296103.823584335
1990106.29254536296234.601504241
#Sta/Elev= 30
       0  1276.2    60.9 1270.07    77.5 1269.31   192.3 1270.09   231.6 1270.18
     255 1268.38   309.6 1269.06   373.5 1266.71     383 1265.21   399.6 1262.99
   430.4 1263.24   451.7 1262.06     463 1259.55     487 1258.59   493.5 1260.11
   496.7 1262.99   498.8 1266.95   502.7 1278.77   506.7 1284.59   511.3 1286.22
   520.4 1283.72   553.9 1282.54   558.2 1283.21   561.8 1285.18   565.7 1288.51
   573.6 1300.43   577.5 1302.78   593.3 1302.82   636.6 1305.86   669.7 1311.14
#Mann= 7 ,-1 , 0
       0     .05       0   192.3     .04       0     383     .08       0
     463    .045       0   493.5     .08       0   520.4    .016       0
   561.8      .1       0
#Block Obstruct= 2 ,-1
  209.31  236.17 1290.15  309.82  345.38 1289.05
Bank Sta=463,493.5
XS Rating Curve= 0 ,0
Exp/Cntr(USF)=0,0
Exp/Cntr=0.3,0.1

Type RM Length L Ch R = 1 ,858     ,177.5,176.4,178.8
XS GIS Cut Line= 3
 1990406.3934563295575.2054659771990018.18952563295893.202302802
1989866.76246048 295990.94159031
#Sta/Elev= 30
       0 1276.46    16.1 1273.94    39.2  1272.2    70.3 1268.53   111.7 1266.82
   168.6  1266.1   180.4 1266.74   215.4 1266.69   236.3 1265.76   292.9 1265.32
   351.2    1266   375.7 1265.54   380.6 1263.36   389.3 1257.51   392.5 1256.34
   418.2 1252.79   452.9 1252.16   458.6 1252.76   465.7  1253.9   474.1 1256.63
   495.3 1258.01   507.6 1261.26   542.7 1262.35   554.4 1265.49   608.6 1265.47
   616.9 1267.71   628.6 1274.41   632.8 1275.25     663 1276.89   682.1 1276.68
#Mann= 4 ,-1 , 0
       0     .05       0   418.2    .045       0   458.6      .1       0
     663    .016       0
Bank Sta=418.2,458.6
XS Rating Curve= 0 ,0
Exp/Cntr(USF)=0,0
Exp/Cntr=0.5,0.3

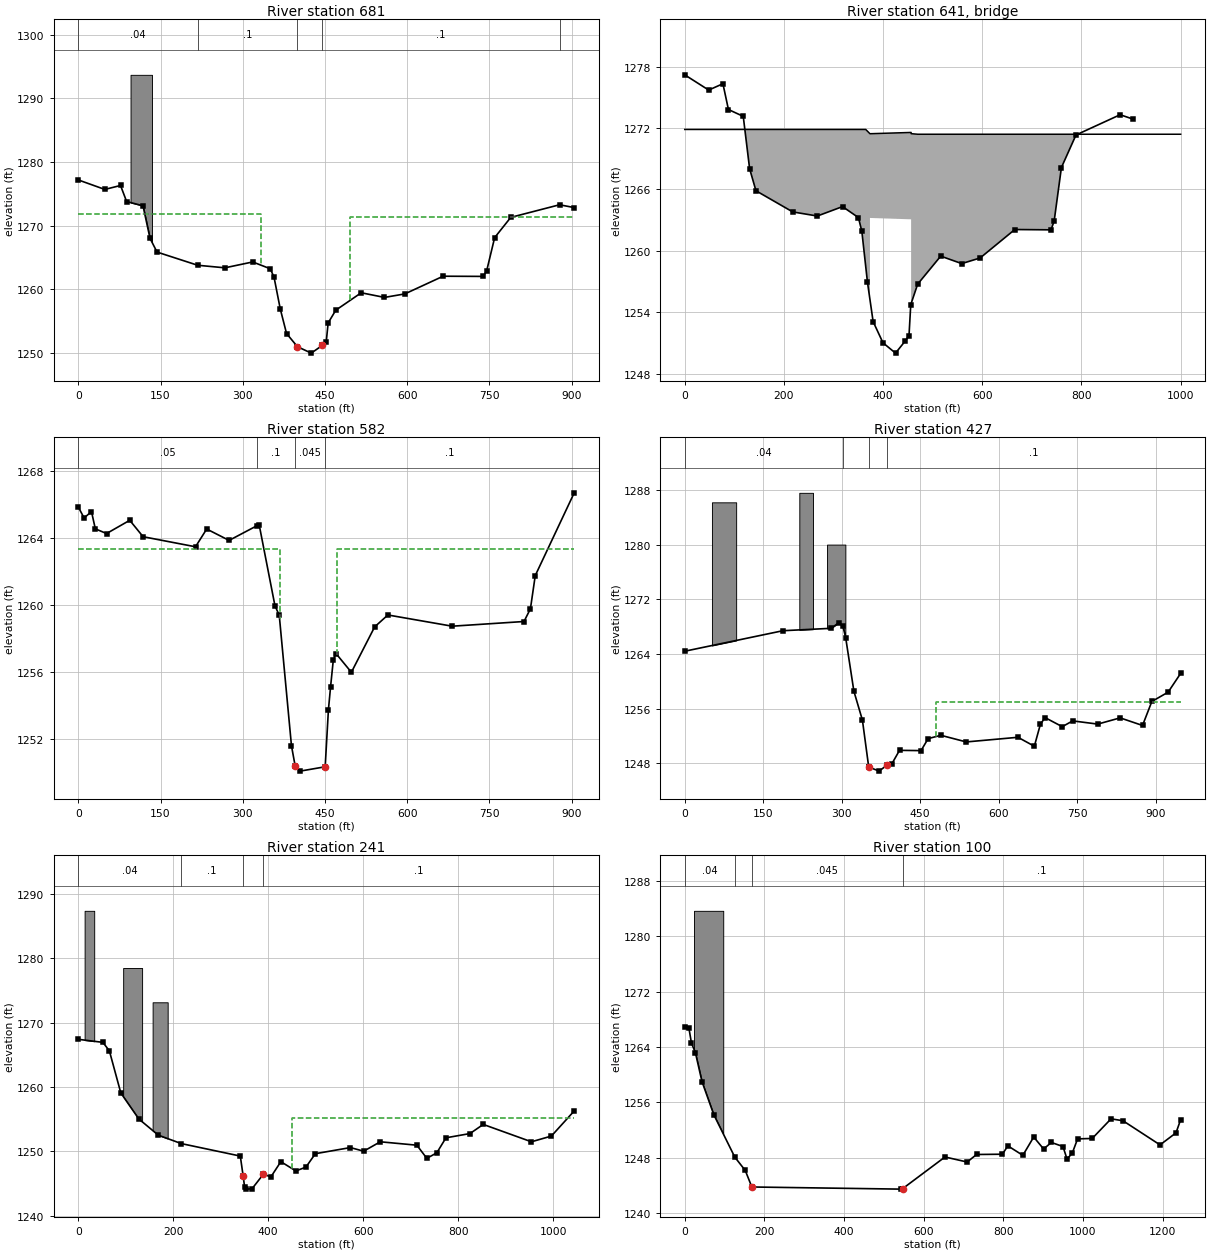
Type RM Length L Ch R = 1 ,681     ,100.4,99.9,99.2
BEGIN DESCRIPTION:
Channel burned from survey data: 54089MEC012BU
END DESCRIPTION:
XS GIS Cut Line= 5
 1990267.3558783295387.9865490581990143.46100681295536.660394846
  1990020.942745295663.3084857031989910.81397034295761.047773212
1989607.95984003 296003.33107746
#Sta/Elev= 30
       0  1277.2    48.3 1275.71      77 1276.33    88.1 1273.81     118 1273.14
   130.8 1268.03   143.6 1265.87   217.8  1263.8   267.4  1263.4   318.2 1264.32
   350.2 1263.25   357.1 1261.92   368.4 1256.96   379.9 1253.08  399.78 1251.01
  425.03    1250  445.04 1251.21  452.25 1251.71   455.8 1254.74   469.7 1256.74
   516.2 1259.48   558.6 1258.75   595.7  1259.3   665.6 1262.08   738.6 1262.05
     745 1262.91   759.6 1268.14     789 1271.32     878  1273.3   904.8 1272.86
#Mann= 5 ,-1 , 0
       0     .04       0   217.8      .1       0  399.78    .045       0
  445.04      .1       0     878    .016       0
#XS Ineff= 2 , 0
           333.5 1271.86   496.5         1271.39
Permanent Ineff=
       F       F
#Block Obstruct= 1 ,-1
   95.24  134.37 1293.71
Bank Sta=399.78,445.04
XS Rating Curve= 0 ,0
Exp/Cntr(USF)=0,0
Exp/Cntr=0.5,0.3

Type RM Length L Ch R = 3 ,641     ,,,
BEGIN DESCRIPTION:
CSX
Bridge Survey Number: 54089MEC010
END DESCRIPTION:
Bridge Culvert--1,0,-1,-1, 0
Deck Dist Width WeirC Skew NumUp NumDn MinLoCord MaxHiCord MaxSubmerge Is_Ogee
40,30,2.6,0, 8, 8, , , 0.98, 0, 0,0,,
       0     365   373.5   373.5   456.5   456.5     470    1000
1271.8611271.8611271.4441271.4441271.569 1271.451271.3931271.393
                        1263.2111263.078
       0     365   378.5   378.5   461.5   461.5     470    1000
1271.8611271.8611271.4441271.4441271.569 1271.431271.3931271.393
                        1263.2111263.078
BR Coef=-1 , 1 , 0 ,, 0 ,,,0.8,0,1.2,0,
WSPro=,,,, 1 ,,,, 0 ,,,, 0 ,,,,-1 ,-1 ,-1 , 0 , 0 , 0 , 0 , 0
BR U #Sta/Elev= 30
       0  1277.2    48.3 1275.71      77 1276.33    88.1 1273.81     118 1273.14
   130.8 1268.03   143.6 1265.87   217.8  1263.8   267.4  1263.4   318.2 1264.32
   350.2 1263.25   357.1 1261.92   368.4 1256.96   379.9 1253.08  399.78 1251.01
  425.03    1250  445.04 1251.21  452.25 1251.71   455.8 1254.74   469.7 1256.74
   516.2 1259.48   558.6 1258.75   595.7  1259.3   665.6 1262.08   738.6 1262.05
     745 1262.91   759.6 1268.14     789 1271.32     878  1273.3   904.8 1272.86
BR U #Mann= 5
       0     .04   217.8      .1  399.78     .04  445.04      .1     878    .016
BR D #Sta/Elev= 30
       0 1265.83    10.5 1265.18      24 1265.56      31 1264.53    51.5 1264.25
    93.8 1265.04   118.2 1264.06   213.8 1263.46   234.2 1264.52   275.1 1263.84
   325.5 1264.71   330.1 1264.75   358.7 1259.95   366.6 1259.37   388.9 1251.58
   395.8 1250.35   404.6 1250.07   450.4 1250.33   456.3 1253.73   460.2 1255.09
   465.2  1256.7   470.1 1257.09   498.2 1255.97   540.7 1258.68   564.8 1259.39
   682.1 1258.72   813.2    1259   824.9 1259.76   833.7 1261.74   904.8 1266.68
BR D #Mann= 4
       0     .05   325.5      .1   395.8     .04   450.4      .1
BC Design=,, 0 ,, 0 ,,,,,,
BC Use User HTab Curves=0
BC User HTab FreeFlow(D)= 0

Type RM Length L Ch R = 1 ,582     ,151.8,154.4,156.8
XS GIS Cut Line= 5
1990213.66810065295304.0133583821990089.77322916 295452.68720417
1989967.25496735295579.335295026 1989857.1261927295677.074582535
1989554.27206239295919.357886783
#Sta/Elev= 30
       0 1265.83    10.5 1265.18      24 1265.56      31 1264.53    51.5 1264.25
    93.8 1265.04   118.2 1264.06   213.8 1263.46   234.2 1264.52   275.1 1263.84
   325.5 1264.71   330.1 1264.75   358.7 1259.95   366.6 1259.37   388.9 1251.58
   395.8 1250.35   404.6 1250.07   450.4 1250.33   456.3 1253.73   460.2 1255.09
   465.2  1256.7   470.1 1257.09   498.2 1255.97   540.7 1258.68   564.8 1259.39
   682.1 1258.72   813.2    1259   824.9 1259.76   833.7 1261.74   904.8 1266.68
#Mann= 4 ,-1 , 0
       0     .05       0   325.5      .1       0   395.8    .045       0
   450.4      .1       0
#XS Ineff= 2 , 0
        367.1667  1263.3472.8333          1263.3
Permanent Ineff=
       F       F
Bank Sta=395.8,450.4
XS Rating Curve= 0 ,0
Exp/Cntr(USF)=0,0
Exp/Cntr=0.5,0.3

Type RM Length L Ch R = 1 ,427     ,196.2,185.8,174.6
XS GIS Cut Line= 4
1990164.11015205295261.3384582021989819.95773125295500.868543083
1989624.47915623295690.8406793681989523.98664935295926.240935199
#Sta/Elev= 30
       0  1264.4   187.7  1267.4   279.6 1267.75   295.1  1268.6   302.1 1268.11
   307.6 1266.39   323.3 1258.55   339.6 1254.32   351.6 1247.48   351.6 1247.47
   371.5 1246.86   386.2 1247.72   395.5 1247.88   410.5  1249.9   451.6 1249.86
   465.3 1251.62   489.6  1252.1   538.1 1251.13   636.9 1251.81   668.2  1250.5
   679.8 1253.72   688.7 1254.69   721.6 1253.36   741.4 1254.21   789.4 1253.74
   832.2 1254.65     875 1253.54   892.8 1257.05   923.9 1258.41   947.8 1261.15
#Mann= 4 ,-1 , 0
       0     .04       0   302.1      .1       0   351.6    .045       0
   386.2      .1       0
#XS Ineff= 2 , 0
                             480         1257.02
Permanent Ineff=
       F       F
#Block Obstruct= 3 ,-1
   51.99   98.27 1286.18  218.97  245.11 1287.57     272     307    1280
Bank Sta=351.6,386.2
XS Rating Curve= 0 ,0
Exp/Cntr(USF)=0,0
Exp/Cntr=0.3,0.1

Type RM Length L Ch R = 1 ,241     ,172.7,141.6,145.9
XS GIS Cut Line= 5
1990111.79898409295188.3781449911989825.46416998295279.234384083
1989738.73775994295335.6753810961989675.41371451295415.518742723
1989488.19479759295920.734496466
#Sta/Elev= 30
       0 1267.42    51.7 1266.95    65.4 1265.63    89.5 1259.08   127.4 1255.04
   168.5 1252.52   216.9 1251.21   341.2 1249.27   347.2 1246.16   350.2 1244.51
   354.2 1244.13   365.9 1244.19   389.4 1246.41   405.9 1246.06   426.6  1248.4
   458.2 1246.96   479.4 1247.55   499.3 1249.64   573.1 1250.59   601.1 1250.03
   636.1 1251.49   713.1 1250.96   734.1 1248.92   755.1 1249.77   774.4 1252.11
     825 1252.77     853 1254.19   954.5 1251.49   996.5 1252.38  1044.6 1256.29
#Mann= 4 ,-1 , 0
       0     .04       0   216.9      .1       0   347.2    .045       0
   389.4      .1       0
#XS Ineff= 1 ,-1
     4501044.574 1255.14
Permanent Ineff=
       F
#Block Obstruct= 3 ,-1
   13.22   33.44  1287.4   94.41  134.32 1278.51  156.48   188.2 1273.18
Bank Sta=347.2,389.4
XS Rating Curve= 0 ,0
Exp/Cntr(USF)=0,0
Exp/Cntr=0.3,0.1

Type RM Length L Ch R = 1 ,100     ,100,100,100
XS GIS Cut Line= 5
1990135.20134871295151.2096835441989789.67231822 295119.54766083
1989617.59610781295258.5852388351989530.86969777295551.803101362
1989462.03921361295916.604667416
#Sta/Elev= 30
       0 1266.91    10.3 1266.78    16.9 1264.57    26.8 1263.17    43.3    1259
    72.9 1254.22   125.7 1248.07     152 1246.14   168.5 1243.75   542.5 1243.44
   547.7 1243.53   653.5 1248.09   709.3 1247.36   732.7 1248.45   797.7 1248.49
   811.4  1249.7     849 1248.33   876.3 1250.98   901.1 1249.25   920.7 1250.19
   949.8  1249.6     960 1247.78   973.1 1248.65   986.5 1250.71  1023.2 1250.77
  1070.5 1253.61  1100.5 1253.33  1193.5 1249.84  1233.6 1251.58  1245.2 1253.48
#Mann= 4 ,-1 , 0
       0     .04       0   125.7      .1       0   168.5    .045       0
   547.7      .1       0
#Block Obstruct= 1 ,-1
   23.22   96.66  1283.7
Bank Sta=168.5,547.7
XS Rating Curve= 0 ,0
Exp/Cntr(USF)=0,0
Exp/Cntr=0.3,0.1
LCMann Table=0

Chan Stop Cuts=-1
Use User Specified Reach Order=0
Composite Channel Slope=5